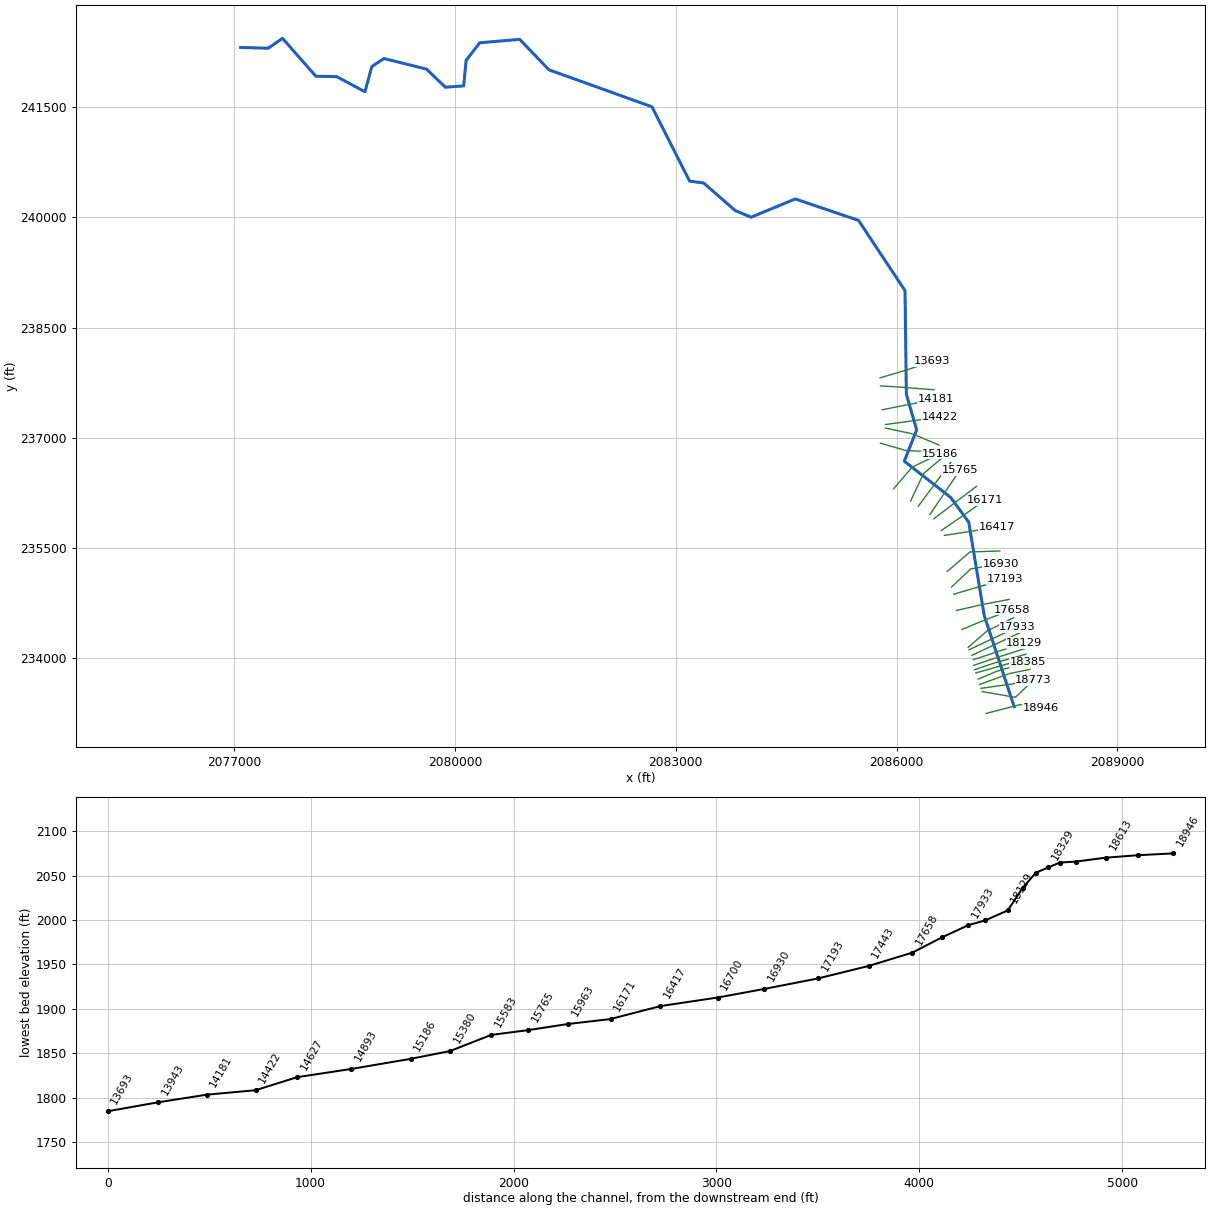
--- BROADRUN.prj (project) ---

Proj Title=BROADRUN
Current Plan=p01
Default Exp/Contr=0,0
English Units
Geom File=g01
Flow File=f01
Plan File=p01
Background Map Layer=Inundation Boundary (10pct Value_0)
BEGIN DESCRIPTION:
Stream Name: Broad Run
Flood Zone: Approximate
Monroe County, West Virginia
HEC-RAS Version: 5.0.7
Vertical Datum: NAVD88
Projection: NAD 1983 StatePlane West Virginia S FIPS 4702 (US Feet)
LiDAR: 2016, 1-meter
Land Use: 2016 NLCD
Hydrology Method:
Regression.
Model Notes:
END DESCRIPTION:
DSS Export Rating Curves= 0
DSS Export Rating Curve Sorted= 0
DSS Export Volume Flow Curves= 0
DXF OffsetX= 0
DXF OffsetY= 0
DXF ScaleX= 0
DXF ScaleY= 0

--- BROADRUN.p01 (plan) ---

Plan Title=Floodplain
Program Version=5.07
Short Identifier=Floodplain
Geom File=g01
Flow File=f01
Subcritical Flow
K Sum by GR= 0
Std Step Tol= 0.01
Critical Tol= 0.01
Num of Std Step Trials= 20
Max Error Tol= 0.3
Flow Tol Ratio= 0.001
Split Flow NTrial= 30
Split Flow Tol= 0.02
Split Flow Ratio= 0.02
Log Output Level= 0
Friction Slope Method= 1
Unsteady Friction Slope Method= 2
Unsteady Bridges Friction Slope Method= 1
Parabolic Critical Depth
Global Vel Dist= 0 , 0 , 0
Global Log Level= 0
CheckData=True
Encroach Param=-1 ,0,0, 0
Mapping Interval=1HOUR
Computation Time Step Use Courant=        0
Computation Time Step Use Time Series=    0
Computation Time Step Count To Double=0
Computation Time Step Max Doubling=0
Computation Time Step Max Halving=0
Computation Time Step Residence Courant=0
Run HTab= 0
Run UNet= 0
Run Sediment= 0
Run PostProcess= 0
Run WQNet= 0
Run RASMapper=-1
UNET Theta= 0
UNET Theta Warmup= 0
UNET ZTol= 0
UNET ZSATol= 0
UNET MxIter= 0
UNET Max Iter WO Improvement= 0
UNET MaxInSteps= 0
UNET DtIC= 0
UNET DtMin= 0
UNET MaxCRTS= 0
UNET WFStab= 0
UNET SFStab= 0
UNET WFX= 1
UNET SFX= 1
UNET 1D Methodology=Finite Difference
UNET DSS MLevel= 1
UNET Pardiso=0
UNET DZMax Abort= 0
UNET Use Existing IB Tables= 0
UNET Froude Reduction=False
UNET Froude Limit= 0
UNET Froude Power= 0
UNET D1 Cores= 0
UNET D2 Coriolis=0
UNET D2 Cores= 0
UNET D2 Theta= 1
UNET D2 Theta Warmup= 1
UNET D2 Z Tol= 0.01
UNET D2 Volume Tol= 0.01
UNET D2 Max Iterations= 20
UNET D2 Equation= 0
UNET D2 RampUpFraction=0.1
UNET D2 TimeSlices= 1
UNET D2 BCVolumeCheck=0
UNET D1D2 MaxIter= 0
UNET D1D2 ZTol=0.01
UNET D1D2 QTol=0.1
UNET D1D2 MinQTol=1
Write IC File= 0
Write IC File at Fixed DateTime=0
Write IC File at Sim End=0
Echo Input=False
Echo Parameters=False
Echo Output=False
Write Detailed= 0
HDF Write Warmup=0
HDF Write Time Slices=0
HDF Flush=0
HDF Face Node Velocities=0
HDF Compression= 1
HDF Chunk Size= 1
HDF Spatial Parts= 1
HDF Use Max Rows=0
HDF Fixed Rows= 1
Calibration Method= 0
Calibration Iterations= 20
Calibration Max Change=0.05
Calibration Tolerance=0.2
Calibration Maximum=1.5
Calibration Minimum=0.5
Calibration Optimization Method= 1
WQ AD Non Conservative
WQ ULTIMATE=-1
WQ Max Comp Step=1HOUR
WQ Output Interval=15MIN
WQ Output Selected Increments= 0
WQ Output face flow=0
WQ Output face velocity=0
WQ Output face area=0
WQ Output face dispersion=0
WQ Output cell volume=0
WQ Output cell surface area=0
WQ Output cell continuity=0
WQ Output cumulative cell continuity=0
WQ Output face conc=0
WQ Output face dconc_dx=0
WQ Output face courant=0
WQ Output face peclet=0
WQ Output face adv mass=0
WQ Output face disp mass=0
WQ Output cell mass=0
WQ Output cell source sink temp=0
WQ Output nsm pathways=0
WQ Output nsm derived pathways=0
WQ Output MaxMinRange=-1
WQ Daily Max Min Mean=-1
WQ Daily Range=0
WQ Daily Time=0
WQ Create Restart=0
WQ Fixed Restart=0
WQ System Summary=0
WQ Write To DSS=0
WQ Use Fixed Temperature=0
Sorting and Armoring Iterations= 10
XS Update Threshold= 0.02
Bed Roughness Predictor= 0
Hydraulics Update Threshold= 0.02
Energy Slope Method= 1
Volume Change Method= 1
Sediment Retention Method= 0
XS Weighting Method= 0
Number of US Weighted Cross Sections= 1
Number of DS Weighted Cross Sections= 1
Upstream XS Weight=0
Main XS Weight=1
Downstream XS Weight=0
Number of DS XS's Weighted with US Boundary= 1
Upstream Boundary Weight= 1
Weight of XSs Associated with US Boundary= 0
Number of US XS's Weighted with DS Boundary= 1
Downstream Boundary Weight= 0.5
Weight of XSs Associated with DS Boundary= 0.5
Percentile Method= 0
Sediment Output Level= 3
Mass or Volume Output= 0
Output Increment Type= 1
Profile and TS Output Increment= 1
XS Output Flag= 0
XS Output Increment= 10
Write Gradation File= 0
Read Gradation Hotstart= 0
Write HDF5 File= 1
Write Binary Output= 1
Write DSS Sediment File= 0
SV Curve= 0
Specific Gage Flag= 0

--- BROADRUN.f01 (steady flow) ---

Flow Title=Flow
Program Version=5.07
Number of Profiles= 6
Profile Names=01pct,10pct,04pct,02pct,0_2pct,01plus
River Rch & RM=BROADRUN,Main            ,18946
     541     285     380     458     756     800
River Rch & RM=BROADRUN,Main            ,18466
     557     294     391     471     778     824
River Rch & RM=BROADRUN,Main            ,17193
     645     342     454     546     899     954
River Rch & RM=BROADRUN,Main            ,16930
     654     348     461     555     912     968
River Rch & RM=BROADRUN,Main            ,16417
     719     383     507     610    1000    1060
River Rch & RM=BROADRUN,Main            ,12359
     916     493     650     779    1270    1360
River Rch & RM=BROADRUN,Main            ,12175
     958     516     680     814    1320    1420
River Rch & RM=BROADRUN,Main            ,11943
    1050     569     748     895    1450    1560
River Rch & RM=BROADRUN,Main            ,5441
    1260     686     899    1070    1730    1860
River Rch & RM=BROADRUN,Main            ,5220
    1310     715     937    1120    1800    1940
Boundary for River Rch & Prof#=BROADRUN,Main            , 1
Up Type= 0
Dn Type= 3
Dn Slope=0.0109
Boundary for River Rch & Prof#=BROADRUN,Main            , 2
Up Type= 0
Dn Type= 3
Dn Slope=0.0109
Boundary for River Rch & Prof#=BROADRUN,Main            , 3
Up Type= 0
Dn Type= 3
Dn Slope=0.0109
Boundary for River Rch & Prof#=BROADRUN,Main            , 4
Up Type= 0
Dn Type= 3
Dn Slope=0.0109
Boundary for River Rch & Prof#=BROADRUN,Main            , 5
Up Type= 0
Dn Type= 3
Dn Slope=0.0109
Boundary for River Rch & Prof#=BROADRUN,Main            , 6
Up Type= 0
Dn Type= 3
Dn Slope=0.0109
DSS Import GetInterval= 0
DSS Import GetPeak= 0
DSS Import FillOption= 0

--- BROADRUN.g01 (geometry) ---

Geom Title=Geometry
Program Version=5.07

River Reach=BROADRUN        ,Main
Reach XY= 30
     2087598.432      233343.729     2087191.531      234585.049
     2086981.027      235853.495     2086735.802      236189.867
     2086105.376      236682.488     2086273.562      237108.921
     2086133.588      237592.861     2086115.142      239002.367
     2085483.631      239957.228     2084624.256      240249.111
     2084023.128       240000.63     2083808.284      240090.691
     2083378.597      240466.125     2083187.624      240491.082
     2082676.557      241502.366     2081276.817      242004.754
     2080878.596       242419.25     2080336.062      242372.592
     2080150.515      242132.792     2080117.963      241786.655
     2079869.482      241768.208      2079612.32      242014.519
     2079032.893      242158.834     2078869.048      242048.156
     2078775.732      241706.359     2078392.702      241912.523
     2078108.414      241917.948     2077656.078      242433.162
     2077460.628      242298.547     2077086.915      242308.964

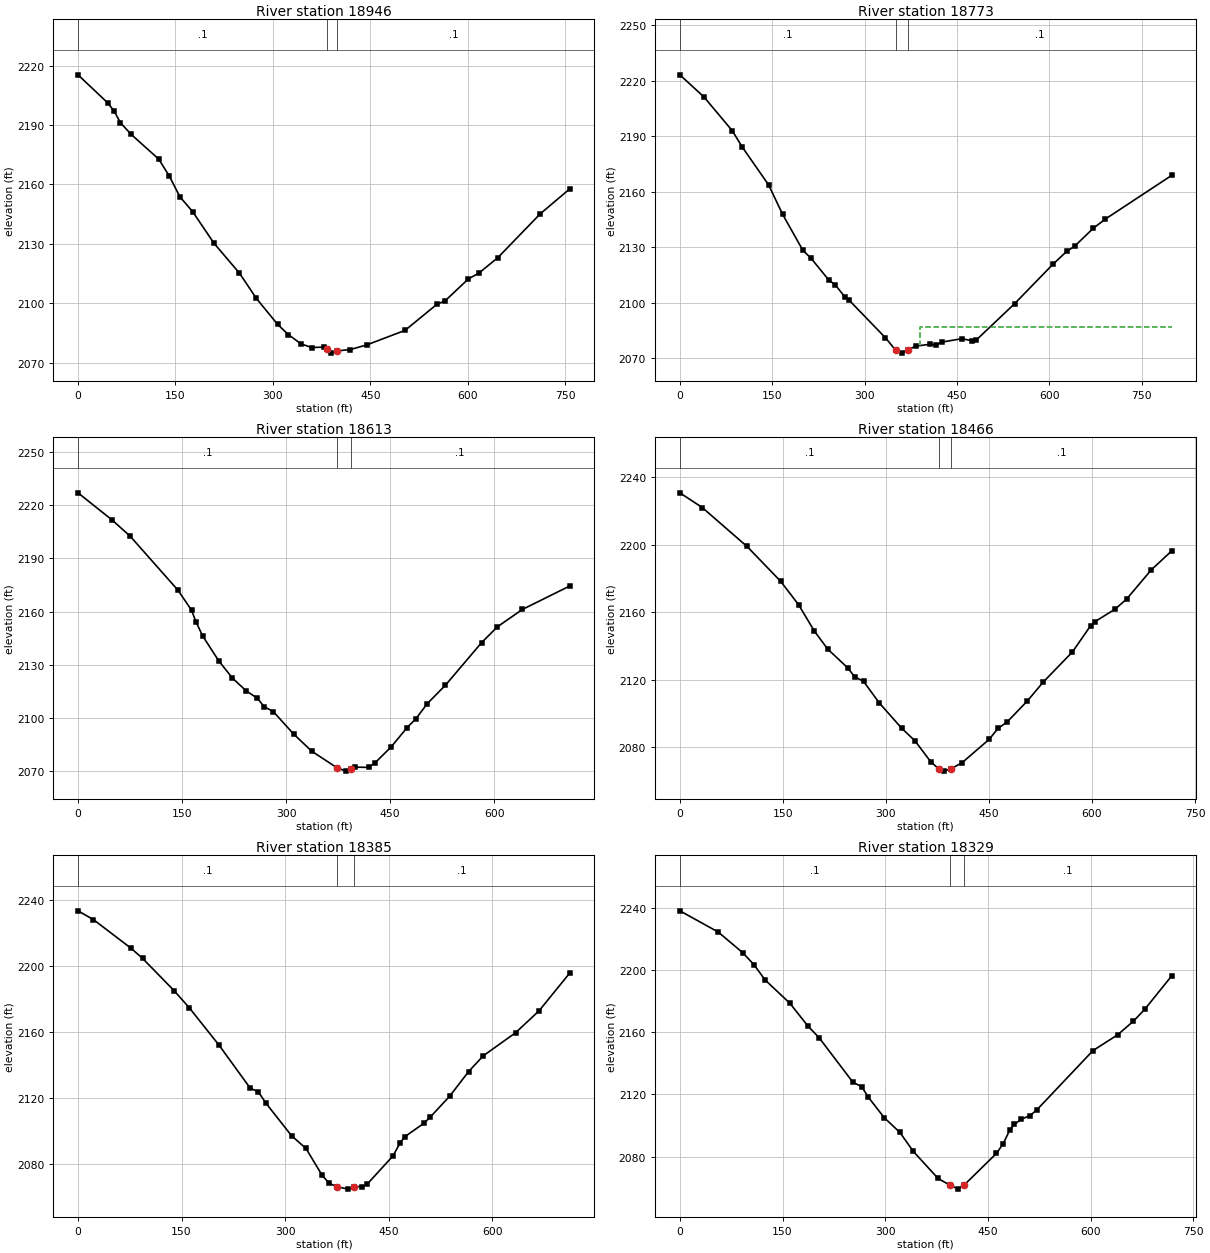
Type RM Length L Ch R = 1 ,18946   ,188.7,172.7,155.1
XS GIS Cut Line= 3
      2087220.58      233253.437     2087689.039      233374.467
     2087957.049      233322.586
#Sta/Elev= 30
       0  2215.3    45.8 2201.12    55.6    2197    65.4 2191.08    81.7 2185.28
   124.2 2172.77   140.6 2164.18   156.9 2153.71   176.5 2146.24   209.2 2130.34
   248.5 2115.21   274.6 2102.43   307.3 2089.33   323.6 2084.24   343.3 2079.53
   359.6 2077.67   379.2 2077.92   383.4 2076.79     389 2074.86   398.4 2076.02
   418.5 2076.61   444.6 2079.03   503.3 2086.34   552.1 2099.44   565.1 2101.28
   600.8 2112.32   617.1 2115.27   646.3  2123.1   711.3 2145.14   756.8 2157.75
#Mann= 3, -1 ,  0
       0     0.1       0   383.4   0.045       0   398.4     0.1       0
Bank Sta=383.4,398.4
XS Rating Curve= 0 ,0
Exp/Cntr=0.3,0.1

Type RM Length L Ch R = 1 ,18773   ,153.4,160.2,165.9
XS GIS Cut Line= 3
     2087162.886      233550.147     2087614.589      233471.565
     2087860.491      233706.792
#Sta/Elev= 30
       0  2223.3    39.3 2211.28    85.2 2193.06   101.5 2184.18   144.1 2163.86
     167 2147.84   199.8 2128.45   212.9 2124.23   242.3 2112.23   252.2 2109.87
   268.5 2103.04   275.1 2101.43     334 2081.15   350.9  2074.3   360.2 2072.87
   370.1 2074.66   383.2 2076.62   406.1 2077.67   415.9 2077.18   425.7 2078.84
   458.5 2080.69   474.8 2079.49   481.4 2079.91   543.6 2099.54   605.7  2120.8
   628.6 2127.92   641.7 2130.79   671.2 2140.25   690.8 2145.25   798.8 2168.92
#Mann= 3, -1 ,  0
       0     0.1       0   350.9   0.045       0   370.1     0.1       0
#XS Ineff= 2 , 0
                          389.68            2087
Permanent Ineff=
       F       F
Bank Sta=350.9,370.1
XS Rating Curve= 0 ,0
Exp/Cntr=0.3,0.1

Type RM Length L Ch R = 1 ,18613   ,141.6,146.8,150
XS GIS Cut Line= 3
      2087147.25      233594.177      2087578.24      233654.073
     2087841.261      233729.594
#Sta/Elev= 30
       0 2227.02    49.1  2211.7    75.2 2202.56     144 2172.16   163.6 2160.85
   170.1 2154.22   179.9 2146.17   202.8 2132.31   222.5 2122.59   242.1 2115.46
   258.5 2111.17   268.3 2106.43   281.4 2103.69   310.8 2090.99     337  2081.3
     373 2072.05   386.1 2070.08   392.9  2071.4   399.1 2072.31   418.8 2072.19
   428.6 2074.93   451.4 2083.76   474.2 2094.54   487.3 2099.75   503.5 2108.18
   529.6 2118.52   581.7 2142.54   604.5 2151.46   640.4 2161.23   708.8 2174.49
#Mann= 3, -1 ,  0
       0     0.1       0     373   0.045       0   392.9     0.1       0
Bank Sta=373,392.9
XS Rating Curve= 0 ,0
Exp/Cntr=0.3,0.1

Type RM Length L Ch R = 1 ,18466   ,82.6,81.3,80.2
XS GIS Cut Line= 3
     2087129.021       233646.26     2087530.063      233793.396
     2087812.615      233852.424
#Sta/Elev= 30
       0  2230.9    32.6 2222.17    97.8 2199.05   146.7 2178.39   172.8  2164.5
   195.7 2148.88   215.2 2138.14   244.6 2126.91   254.4 2121.72   267.4 2118.97
   290.2 2106.22   322.8 2091.21   342.4 2083.61   365.2 2071.25   377.2 2066.92
   384.8  2065.7   394.6 2067.03   410.9 2070.74   450.1 2084.51   463.3  2091.1
   476.4 2094.89   505.9 2107.39   528.9 2118.54   571.5 2136.49   597.8 2151.96
   604.3 2154.45   633.8 2161.94   650.2  2167.8   686.3 2185.21   715.8 2196.38
#Mann= 3, -1 ,  0
       0     0.1       0   377.2   0.045       0   394.6     0.1       0
Bank Sta=377.2,394.6
XS Rating Curve= 0 ,0
Exp/Cntr=0.3,0.1

Type RM Length L Ch R = 1 ,18385   ,56.1,55.9,56.3
XS GIS Cut Line= 4
2087108.61737368233719.0899360572087362.05236192233825.993422003
2087646.82113052 233908.93578179 2087782.2936515233946.720634581
#Sta/Elev= 30
       0 2233.51    22.4 2228.17    76.8  2210.8    93.7 2204.58   139.4 2184.95
   161.3 2174.62   204.5 2151.85   249.6 2125.78     261 2123.75   272.1 2116.84
   309.4 2096.95   330.2 2089.28   353.8 2072.87   364.1 2068.05   375.2 2066.02
     391 2064.58   399.52066.072   411.9 2066.17   418.8 2067.56   456.4 2084.81
   466.6 2092.75   473.4 2096.39   500.8  2104.5   510.1 2108.25   538.4 2121.01
   565.7 2135.89     587  2145.5   633.8  2159.5   667.9 2172.85   712.3 2195.76
#Mann= 3, -1 ,  0
       0     0.1       0   375.2   0.045       0   399.5     0.1       0
Bank Sta=375.2,399.5
XS Rating Curve= 0 ,0
Exp/Cntr(USF)=0,0
Exp/Cntr=0.3,0.1

Type RM Length L Ch R = 1 ,18329   ,61.4,60.6,60.9
XS GIS Cut Line= 2
     2087076.704      233802.507     2087767.521      233999.883
#Sta/Elev= 30
       0 2237.94    55.8 2224.37    91.9 2211.02   108.3  2203.3   124.7 2193.43
   160.8  2178.5     187 2163.92   203.4  2156.4   252.6 2127.87   265.7 2124.82
   275.6 2118.01   298.5 2105.02   321.5 2095.48   341.2 2083.24   377.3 2065.89
  395.37 2061.38   406.8 2059.03  414.82 2061.43   462.6 2082.01   472.4 2088.21
   482.2 2097.15   488.8 2100.63   498.7 2103.93   511.8 2106.35   521.6    2110
   603.6 2148.08   639.7 2158.25   662.7 2167.01   679.1 2174.54   718.5 2196.05
#Mann= 3, -1 ,  0
       0     0.1       0  395.37   0.045       0  414.82     0.1       0
Bank Sta=395.37,414.82
XS Rating Curve= 0 ,0
Exp/Cntr=0.3,0.1

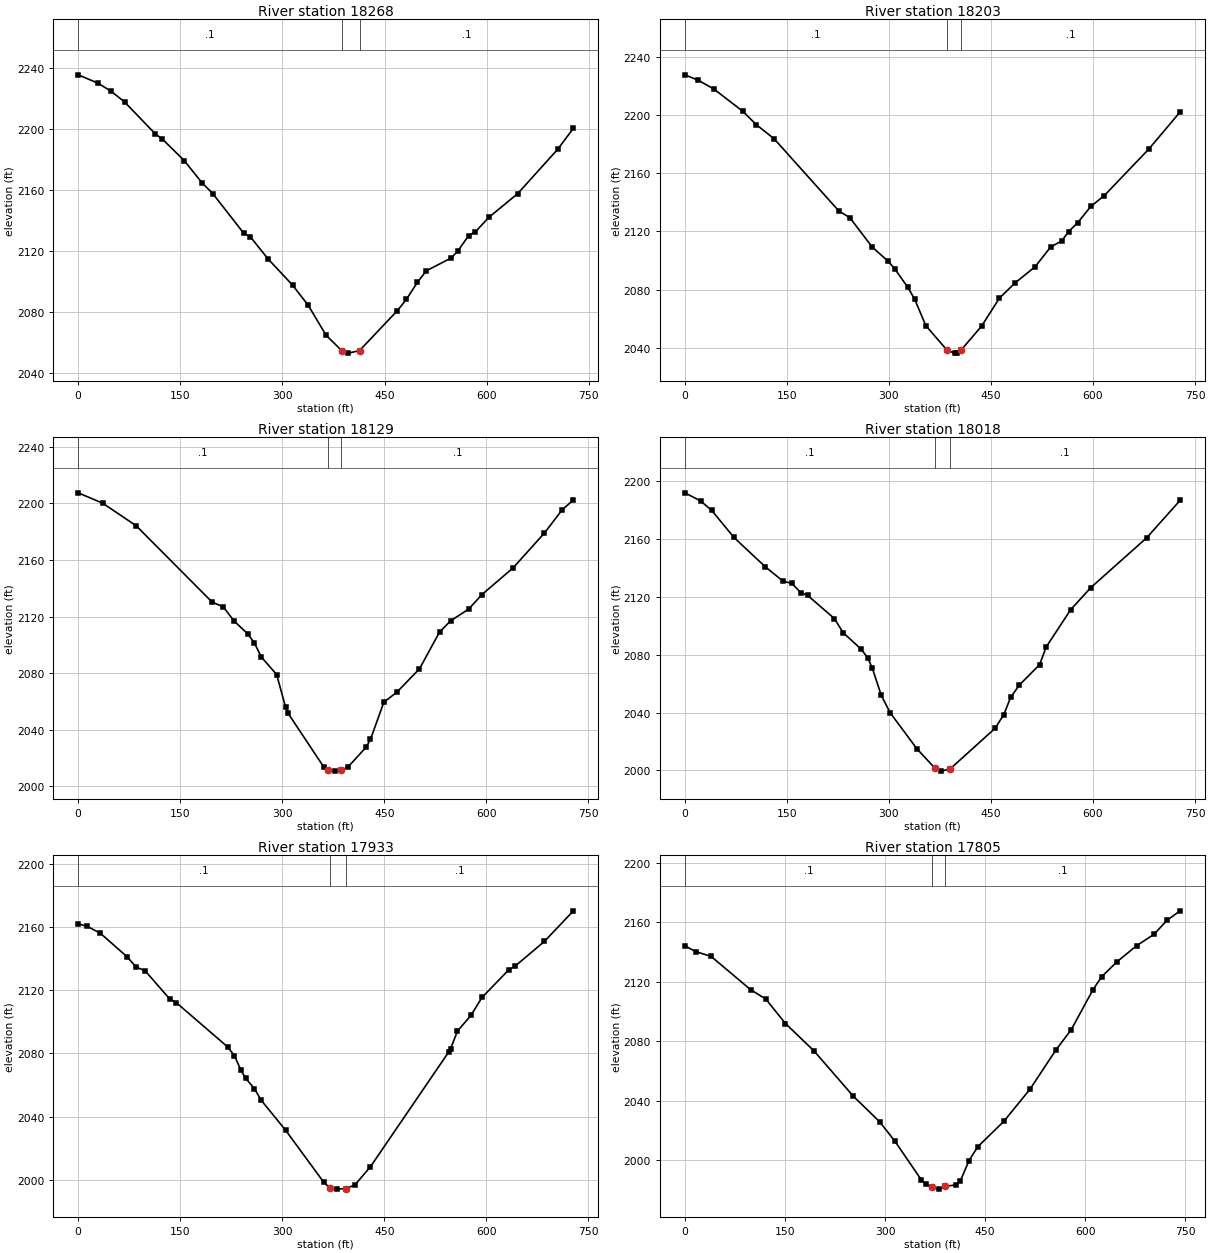
Type RM Length L Ch R = 1 ,18268   ,64.5,65.1,66
XS GIS Cut Line= 3
     2087062.887      233848.137     2087314.621      233933.927
     2087759.065      234058.059
#Sta/Elev= 30
       0 2235.61    29.2 2230.12    48.6 2224.76    68.1 2217.85   113.5 2196.81
   123.2  2193.7   155.7 2179.46   181.6 2165.02   197.8 2157.72   243.2  2131.8
     253 2129.41     279 2114.92     315 2097.77     338 2084.52   364.1 2064.97
     387 2054.94   396.9 2053.26   413.2 2054.91   468.9 2081.15     482 2088.42
   498.3 2099.71   511.4 2107.19   547.4  2115.5   557.2 2119.91   573.6 2130.31
   583.4 2132.74     603 2142.13   645.6  2157.8   704.5 2186.93   727.4 2200.61
#Mann= 3, -1 ,  0
       0     0.1       0     387   0.045       0   413.2     0.1       0
Bank Sta=387,413.2
XS Rating Curve= 0 ,0
Exp/Cntr=0.3,0.1

Type RM Length L Ch R = 1 ,18203   ,73.9,73.9,74
XS GIS Cut Line= 3
     2087051.168      233908.033     2087396.485      234023.138
     2087743.054      234134.513
#Sta/Elev= 30
       0 2227.54    19.7 2223.82    42.6  2217.8    85.3 2202.44   104.9 2193.36
   131.2 2183.61   226.3 2134.06   242.7 2129.32   275.5 2109.18   298.4 2099.67
   308.2  2094.5   327.9 2081.46   337.8 2073.44   354.2 2055.28   385.7 2038.23
   396.8 2036.37   400.1 2036.42   406.6 2038.77   436.1 2054.86   462.4 2074.14
   485.3 2084.55   514.8  2095.7   537.8 2109.33   554.2 2113.53     564 2119.84
   577.2 2125.82   596.8 2137.15   616.5 2144.55   682.1 2176.59     728    2202
#Mann= 3, -1 ,  0
       0     0.1       0   385.7   0.045       0   406.6     0.1       0
Bank Sta=385.7,406.6
XS Rating Curve= 0 ,0
Exp/Cntr=0.3,0.1

Type RM Length L Ch R = 1 ,18129   ,108.5,111.7,113.9
XS GIS Cut Line= 3
     2087044.658      233983.554     2087389.974      234098.659
     2087736.544      234210.034
#Sta/Elev= 30
       0 2207.43    36.1 2200.08    85.3 2184.14   196.8 2130.25   213.2  2126.9
   229.6 2116.61   249.2 2107.82   259.1 2101.35   268.9 2091.64   291.8 2078.97
     305 2055.76   308.2  2051.9   360.7  2013.9   367.3 2011.74   377.1 2010.78
     387 2011.47   396.8  2013.8     423 2027.54   429.6 2033.14   449.3 2059.42
   468.9 2066.76   501.7 2083.07   531.2 2109.03   547.6 2117.04   573.9 2125.22
   593.6 2135.56   639.5 2154.49   685.4 2179.04   711.6 2195.52     728 2202.43
#Mann= 3, -1 ,  0
       0     0.1       0   367.3   0.045       0     387     0.1       0
Bank Sta=367.3,387
XS Rating Curve= 0 ,0
Exp/Cntr=0.3,0.1

Type RM Length L Ch R = 1 ,18018   ,85,85,85
XS GIS Cut Line= 3
      2087024.05      234042.718     2087353.263      234198.007
     2087682.476      234353.297
#Sta/Elev= 30
       0 2191.64      23 2186.08    39.4 2179.56    72.1 2160.88     118 2140.68
   144.3 2130.68   157.4 2129.13   170.5 2122.67   180.4 2120.89   219.7  2104.9
   232.8 2095.08   259.1 2083.78   268.9  2077.7   275.5 2070.71   288.6 2052.04
   301.7  2039.9     341 2015.04  368.03 2001.38   377.1 1999.56   390.2  2001.2
   455.8    2029   468.9 2038.58   478.8 2050.39   491.9  2059.1   521.4 2073.02
   531.2 2085.28   567.3  2111.1   596.8 2126.26   678.8 2160.56     728 2186.44
#Mann= 3, -1 ,  0
       0     0.1       0  368.03   0.045       0   390.2     0.1       0
Bank Sta=368.03,390.2
XS Rating Curve= 0 ,0
Exp/Cntr=0.3,0.1

Type RM Length L Ch R = 1 ,17933   ,126.8,127.3,127.8
XS GIS Cut Line= 3
     2086984.987      234118.239     2087314.201      234273.528
     2087643.414      234428.817
#Sta/Elev= 30
       0 2162.05    13.1 2160.62    32.8  2156.1    72.1 2141.15    85.3 2134.69
    98.4 2132.39   134.4 2114.56   144.3 2112.17   219.7 2084.12   229.6 2078.68
   239.4 2069.19     246 2064.37   259.1 2057.68   268.9 2050.41     305 2031.28
   360.7 1998.51   370.6 1994.51   380.4 1994.01   393.5 1994.37   406.6 1996.58
   429.6 2008.19   544.4 2080.74   547.6 2083.11   557.5  2094.1   577.2 2104.04
   593.6 2115.45   632.9 2132.97   642.7 2135.47   685.4 2151.01     728 2170.37
#Mann= 3, -1 ,  0
       0     0.1       0   370.6   0.045       0   393.5     0.1       0
Bank Sta=370.6,393.5
XS Rating Curve= 0 ,0
Exp/Cntr=0.3,0.1

Type RM Length L Ch R = 1 ,17805   ,150.2,147.3,146.3
XS GIS Cut Line= 3
     2086974.298       234152.01     2087226.678      234371.521
     2087591.261      234553.812
#Sta/Elev= 30
       0 2144.18    16.4 2140.28    39.4 2137.04    98.4 2114.72   121.3 2108.37
   150.8  2091.9   193.5  2073.5   252.5    2043   291.9 2025.83   314.8 2012.73
     354 1986.98   360.6 1983.84   370.4  1981.9   380.1 1980.53   389.9 1982.37
   406.2 1983.38   412.8 1986.01   425.8 1999.71   438.8 2008.97     478 2026.13
   517.1 2047.69   556.2 2074.22   579.1 2087.88   611.7 2114.78   624.7 2123.43
   647.5 2133.44   676.9 2144.24     703  2151.9   722.5 2161.34   742.1 2167.71
#Mann= 3, -1 ,  0
       0     0.1       0   370.4   0.045       0   389.9     0.1       0
Bank Sta=370.4,389.9
XS Rating Curve= 0 ,0
Exp/Cntr=0.3,0.1

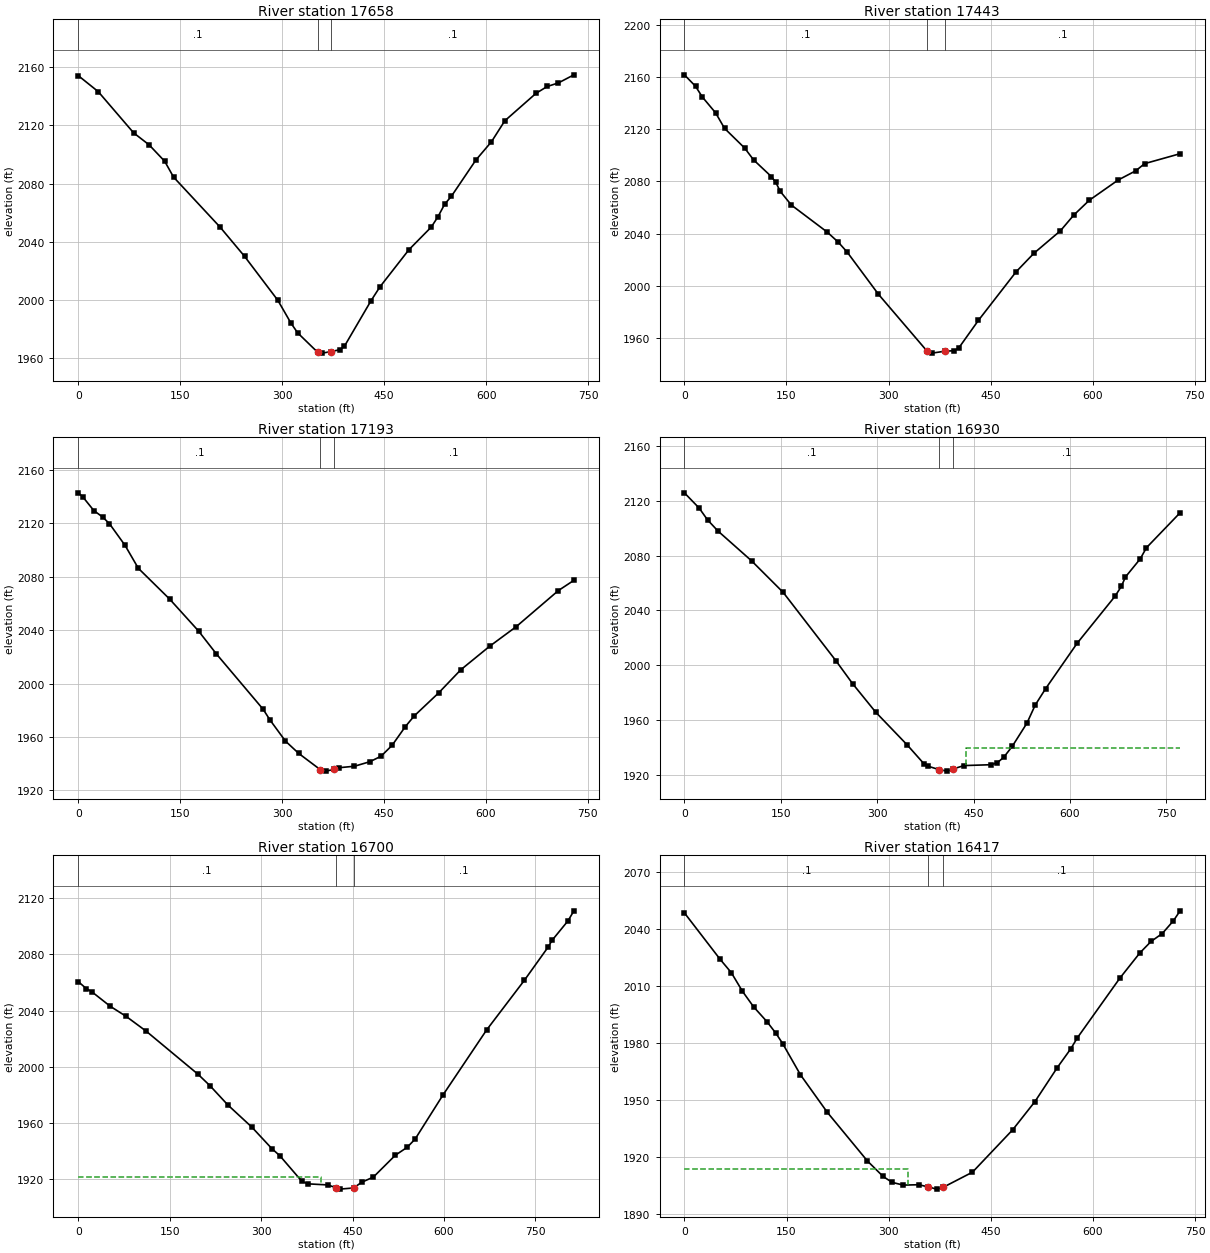
Type RM Length L Ch R = 1 ,17658   ,217,214.6,209.7
XS GIS Cut Line= 3
     2086888.947      234394.191      2087226.03      234534.719
     2087567.202      234660.757
#Sta/Elev= 30
       0 2154.27    29.4 2143.25    81.5 2114.86   104.3 2106.59   127.2 2095.29
   140.2 2084.42   208.7 2049.96   244.6 2029.89   293.5 1999.66     313 1983.81
   322.8 1977.17   352.2 1963.82   358.7 1963.27   371.8 1964.32   384.9 1965.65
   391.4 1967.95   430.7 1999.42   443.8 2008.94   486.4 2034.48   519.2 2050.04
     529  2057.1   538.9  2065.8   548.7 2071.17   584.7 2096.11   607.7 2108.74
   627.3 2123.15   673.2 2142.06   689.6 2146.76     706  2149.2   728.9 2154.79
#Mann= 3, -1 ,  0
       0     0.1       0   352.2   0.045       0   371.8     0.1       0
Bank Sta=352.2,371.8
XS Rating Curve= 0 ,0
Exp/Cntr=0.3,0.1

Type RM Length L Ch R = 1 ,17443   ,248.3,250,251.2
XS GIS Cut Line= 3
      2086817.92      234654.703     2087172.926      234734.338
     2087531.086      234803.037
#Sta/Elev= 30
       0 2161.59    16.4  2152.8    26.2 2144.72    45.9 2132.44      59 2120.57
    88.5 2105.53   101.6 2096.47   127.8 2083.63   134.4  2079.1   140.9 2072.26
   157.3 2061.76   209.8 2041.13   226.2 2033.34   239.3  2025.7   285.2 1993.43
   356.3 1950.08   363.8 1948.34   383.4 1949.84   396.4  1950.2   402.9 1952.05
   432.2  1973.5   487.6 2010.71   513.6 2024.81   552.7 2042.12   572.2 2054.08
     595 2065.45   637.4 2080.96   663.4 2088.07   676.4 2093.54   728.5 2101.15
#Mann= 3, -1 ,  0
       0     0.1       0   356.3   0.045       0   383.4     0.1       0
Bank Sta=356.3,383.4
XS Rating Curve= 0 ,0
Exp/Cntr=0.3,0.1

Type RM Length L Ch R = 1 ,17193   ,265.1,263.6,259.3
XS GIS Cut Line= 3
      2086776.42      234873.662     2087125.618      234976.383
     2087477.181      235075.961
#Sta/Elev= 30
       0 2142.97     6.6 2140.05      23 2129.67    36.1 2124.75    45.9 2119.88
    68.9  2103.6    88.5 2086.37   134.4 2063.38   177.1 2039.35   203.3  2022.2
   272.2 1980.64     282  1972.8     305  1956.8   324.6 1947.53   356.5  1935.3
     364  1934.3     377 1935.63   383.6 1936.85   406.4 1937.96   429.2 1941.36
   445.6 1945.47   461.9 1953.64   481.4 1967.68   494.5 1975.71   530.4 1992.96
     563  2010.3   605.4 2027.91   644.6 2042.64   706.6  2069.7   729.4 2077.36
#Mann= 3, -1 ,  0
       0     0.1       0   356.5   0.045       0     377     0.1       0
Bank Sta=356.5,377
XS Rating Curve= 0 ,0
Exp/Cntr=0.3,0.1

Type RM Length L Ch R = 1 ,16930   ,230.9,229.9,224.6
XS GIS Cut Line= 3
     2086747.511      234972.215     2087009.664      235218.743
     2087415.876      235284.452
#Sta/Elev= 30
       0    2126    22.9 2114.89      36 2106.24    52.3 2098.06   104.7 2076.22
   153.8 2053.18   235.6 2003.38   261.7 1986.53   297.7 1965.67   346.8 1941.68
   372.9 1927.88   379.5 1926.12   396.2 1923.67   408.8 1922.56   418.6  1924.2
     435 1926.62   477.4 1927.25   487.2 1928.76     497 1932.72   510.1  1940.6
     533 1957.58     546 1970.89   562.3 1982.96   611.3  2016.1   670.1 2050.36
   679.9 2057.54   686.4  2064.5   709.3 2077.68   719.1  2085.9   771.4 2111.42
#Mann= 3, -1 ,  0
       0     0.1       0   396.2   0.045       0   418.6     0.1       0
#XS Ineff= 2 , 0
                          438.97         1939.67
Permanent Ineff=
       F       F
Bank Sta=396.2,418.6
XS Rating Curve= 0 ,0
Exp/Cntr=0.3,0.1

Type RM Length L Ch R = 1 ,16700   ,280.7,282.6,285.2
XS GIS Cut Line= 3
       2086688.7      235183.749     2086996.727      235448.412
     2087403.441       235461.87
#Sta/Elev= 30
       0 2060.65    13.1 2055.68    22.9 2053.19    52.4 2043.09    78.6 2035.86
   111.4 2025.36   196.5 1994.66   216.2 1986.48   245.6 1972.74   284.9 1956.98
   317.7 1941.69   330.8 1936.62   366.8 1918.47   376.6 1916.66   409.4 1915.87
   422.4 1913.96   428.9 1912.89   451.7 1913.72   464.7  1917.7   484.2  1921.5
     520 1936.96   539.6 1942.68   552.6 1948.51   598.2 1979.85   669.8 2026.16
   731.7 2061.49   770.7 2085.17   777.2 2089.99   803.3 2103.84     813 2110.99
#Mann= 3, -1 ,  0
       0     0.1       0   422.4   0.045       0   451.7     0.1       0
#XS Ineff= 2 , 0
          398.15 1921.36
Permanent Ineff=
       F       F
Bank Sta=422.4,451.7
XS Rating Curve= 0 ,0
Exp/Cntr=0.3,0.1

Type RM Length L Ch R = 1 ,16417   ,237,246.1,255.6
XS GIS Cut Line= 3
     2086649.437      235673.744     2087009.265      235728.937
     2087368.306      235788.777
#Sta/Elev= 30
       0 2048.57    52.5 2024.13    68.9 2017.13    85.3  2007.3   101.7 1999.12
   121.4 1991.29   134.5 1985.18   144.3 1979.84   170.5 1963.38   209.9 1943.66
   268.9 1918.03   291.9 1909.91     305 1906.83   321.4 1905.37   344.4 1905.58
   358.2  1904.4   370.6 1903.26   380.4 1904.28   423.1 1912.18   482.1 1934.45
   514.9 1949.34   547.7 1967.21   567.4 1977.03   577.2 1982.88   639.5 2014.21
     669 2027.54   685.4 2033.54   701.8 2037.69   718.2  2044.4     728 2049.64
#Mann= 3, -1 ,  0
       0     0.1       0   358.2   0.045       0   380.4     0.1       0
#XS Ineff= 2 , 0
          328.94 1913.91
Permanent Ineff=
       F       F
Bank Sta=358.2,380.4
XS Rating Curve= 0 ,0
Exp/Cntr=0.3,0.1

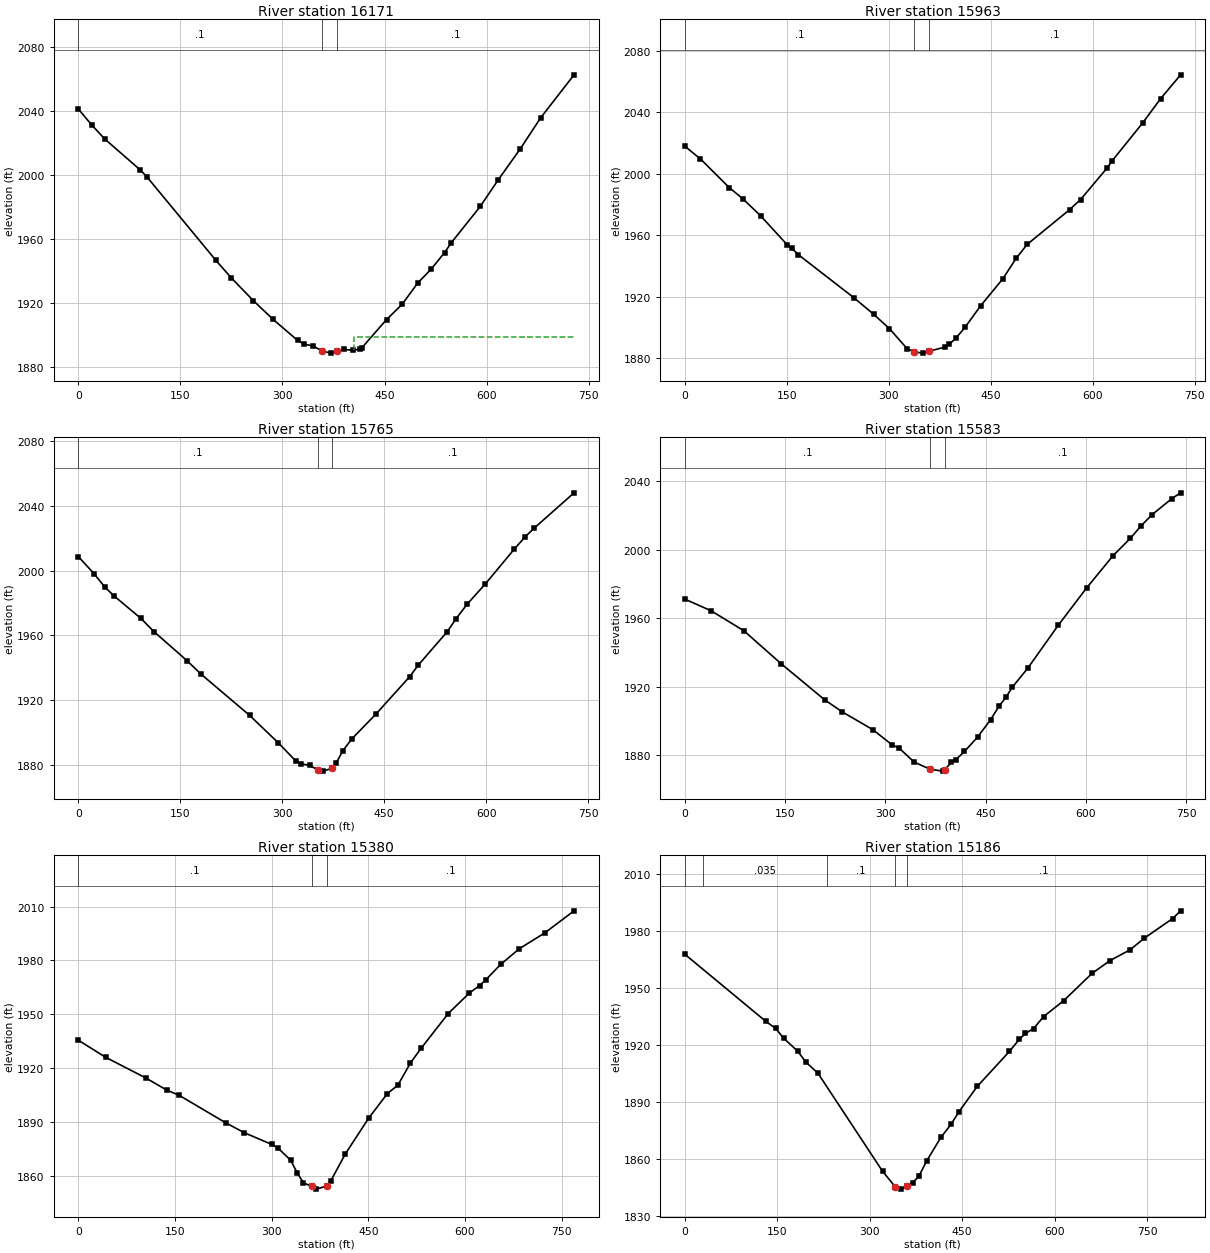
Type RM Length L Ch R = 1 ,16171   ,206,207.7,207.9
XS GIS Cut Line= 3
     2086608.095      235740.017     2086908.367       235946.51
     2087207.116      236154.335
#Sta/Elev= 30
       0 2041.42    19.5 2031.54      39 2022.61    91.1 2003.27   100.9 1998.91
   201.7 1946.95   224.5  1935.9     257 1921.59   286.3 1909.75   322.1 1896.69
   331.9 1894.29   344.9 1893.19   357.9 1890.11     371 1888.68   379.4 1889.71
   390.6 1890.98   403.8 1890.46   413.6 1891.25   416.9 1892.14   452.9  1909.7
   475.9 1919.28   498.8 1932.59   518.5 1941.25   538.2 1951.62     548 1957.73
   590.6 1980.45   616.9 1997.06   649.7 2016.67   679.2 2035.84   728.4 2062.82
#Mann= 3, -1 ,  0
       0     0.1       0   357.9   0.045       0   379.4     0.1       0
#XS Ineff= 2 , 0
                          405.73          1898.7
Permanent Ineff=
       F       F
Bank Sta=357.9,379.4
XS Rating Curve= 0 ,0
Exp/Cntr=0.3,0.1

Type RM Length L Ch R = 1 ,15963   ,192.4,198.4,205.4
XS GIS Cut Line= 2
     2086506.191      235899.299     2087086.443      236341.091
#Sta/Elev= 30
       0 2017.91    22.9 2009.67    65.4 1990.94      85  1983.8   111.2 1972.73
   150.4 1953.78     157 1951.65   166.8 1947.33   248.6 1919.27     278 1908.37
   300.9 1899.15     327    1886   337.7 1883.97   349.9 1883.18   359.7 1884.47
   382.6 1887.14   389.2 1889.06     399 1893.12   412.1 1899.99     435    1914
   467.7  1931.6   487.3 1944.93   503.6 1954.06   565.8 1976.57   582.1 1983.25
   621.4 2003.94   627.9 2008.09   673.7 2033.28   699.9    2049   729.3 2064.48
#Mann= 3, -1 ,  0
       0     0.1       0   337.7   0.045       0   359.7     0.1       0
Bank Sta=337.7,359.7
XS Rating Curve= 0 ,0
Exp/Cntr=0.3,0.1

Type RM Length L Ch R = 1 ,15765   ,182.6,182.2,180.7
XS GIS Cut Line= 2
     2086453.927      235958.331     2086863.034      236562.199
#Sta/Elev= 30
       0  2008.7    22.9 1998.26    39.2 1989.82    52.3  1984.5    91.6 1970.72
   111.2  1962.4   160.3 1944.31   179.9 1936.35   251.9 1910.71   294.4 1893.64
   320.5 1882.26   327.1  1880.8   340.2 1879.74   352.2 1877.11   359.8 1876.23
   372.9  1877.9   379.4 1881.19   389.2  1888.8   402.3 1896.07   438.3 1911.63
   487.4  1934.5   500.4 1941.79     543 1962.44     556 1970.47   572.4 1979.46
   598.6 1991.68   641.1 2013.14   657.4  2020.9   670.5 2026.18   729.4 2048.09
#Mann= 3, -1 ,  0
       0     0.1       0   352.2   0.045       0   372.9     0.1       0
Bank Sta=352.2,372.9
XS Rating Curve= 0 ,0
Exp/Cntr=0.3,0.1

Type RM Length L Ch R = 1 ,15583   ,199.3,203.3,207.6
XS GIS Cut Line= 2
     2086296.216      236070.877     2086737.322      236667.492
#Sta/Elev= 30
       0 1971.12    39.2 1964.33    88.2 1952.71   143.8 1933.54   209.2  1912.4
   235.3 1905.43   281.1 1895.07   310.5 1886.04   320.3 1884.39   343.2  1876.1
   367.1 1871.94   385.7 1870.84     389 1871.64   398.8 1876.01   405.3 1877.44
   418.4 1882.29     438 1890.65   457.6 1900.86   470.7 1909.02   480.5 1913.89
   490.3 1919.89   513.2 1930.87   558.9 1955.93   601.4 1977.74   640.6 1996.37
   666.8  2006.6   683.1 2014.01   699.5 2020.45   728.9 2029.78     742 2033.12
#Mann= 3, -1 ,  0
       0     0.1       0   367.1   0.045       0     389     0.1       0
Bank Sta=367.1,389
XS Rating Curve= 0 ,0
Exp/Cntr=0.3,0.1

Type RM Length L Ch R = 1 ,15380   ,197.7,193.9,186.7
XS GIS Cut Line= 3
     2086190.774      236140.724     2086365.721      236513.047
     2086639.189       236744.05
#Sta/Elev= 30
       0  1935.6    42.4 1926.08   104.5 1914.61   137.1 1907.84   156.7 1904.87
   228.5 1889.65   257.9 1884.04   300.4 1877.53   310.2 1875.44   329.8 1868.65
   339.6 1861.76   349.3 1856.22   362.4 1854.18   368.9 1852.67   385.3 1854.33
   391.8 1857.22   414.6 1872.39   450.4 1892.05   479.7 1905.89     496 1910.56
   515.5 1922.91   531.8 1930.98   574.1 1950.42   606.6 1961.75   622.9 1966.05
   632.7 1969.32   655.4 1977.75   684.7 1986.58   723.8 1995.29   769.4 2007.63
#Mann= 3, -1 ,  0
       0     0.1       0   362.4   0.045       0   385.3     0.1       0
Bank Sta=362.4,385.3
XS Rating Curve= 0 ,0
Exp/Cntr=0.3,0.1

Type RM Length L Ch R = 1 ,15186   ,313.6,292.4,268.8
XS GIS Cut Line= 3
     2085960.592      236307.936     2086211.708      236601.268
     2086587.737      236784.773
#Sta/Elev= 30
       0 1967.83   130.9 1932.57   147.3 1928.71   160.4 1923.51   183.2 1916.67
   196.3 1910.97     216 1905.06   320.7  1853.4   341.4 1845.15   350.1 1843.94
     360 1845.35   369.8 1847.41   379.6 1850.66   392.7    1859   415.6  1871.3
   431.9  1878.1     445 1884.88   474.4 1898.11   526.7 1916.59     543 1923.09
   552.8 1926.07   565.9 1928.67   582.3 1935.01     615 1943.45   660.7 1957.75
   690.1 1964.56   722.8 1970.28   745.7 1976.36   791.5 1986.69   804.6 1990.79
#Mann= 5, -1 ,  0
       0     0.1       0      30   0.035       0     230     0.1       0
   341.4   0.045       0     360     0.1       0
Bank Sta=341.4,360
XS Rating Curve= 0 ,0
Exp/Cntr=0.3,0.1

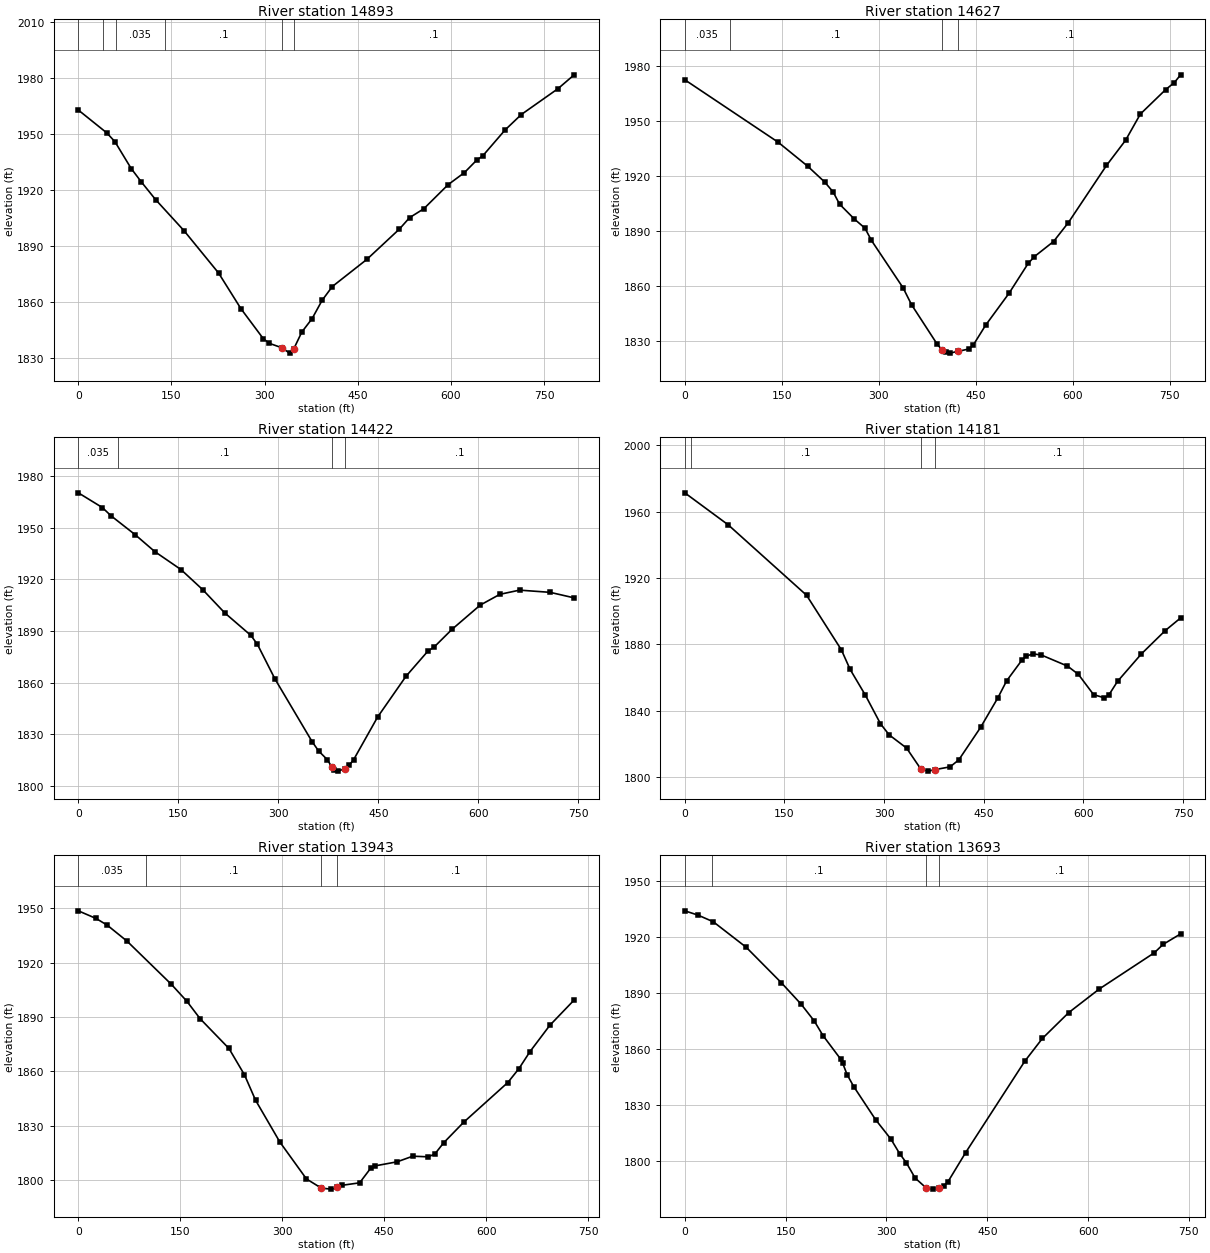
Type RM Length L Ch R = 1 ,14893   ,267.9,266.3,263.8
XS GIS Cut Line= 3
     2085780.817      236928.296     2086129.775      236827.602
     2086564.593      236809.111
#Sta/Elev= 30
       0 1962.99    45.8 1950.74    58.9 1946.03    85.1 1931.62   101.4 1924.45
   124.3 1914.98   170.2 1898.26   225.8 1875.57   261.8 1856.43   297.8 1840.35
   307.6 1837.83   327.2 1835.52   340.3 1832.58   346.8  1834.8   359.9 1843.92
   376.3 1851.03   392.6 1860.93     409 1868.31   464.6 1882.87     517 1899.13
   533.4 1905.26   556.3 1910.03   595.5 1922.97   621.7 1929.43   641.3 1936.06
   651.2 1938.41   687.2 1952.31   713.3 1960.58   772.2 1974.41   798.4 1981.88
#Mann= 6, -1 ,  0
       0   0.035       0      40     0.1       0      60   0.035       0
     140     0.1       0   327.2   0.045       0   346.8     0.1       0
Bank Sta=327.2,346.8
XS Rating Curve= 0 ,0
Exp/Cntr=0.3,0.1

Type RM Length L Ch R = 1 ,14627   ,195.5,205.3,218.8
XS GIS Cut Line= 3
     2085849.502      237133.897     2086211.708      237055.832
     2086577.316      236902.484
#Sta/Elev= 30
       0 1972.34   144.3 1938.34   190.2 1925.21   216.4 1916.62   229.5 1911.19
   239.4 1904.57   262.3 1896.44   278.7 1891.48   288.6 1884.86   337.7 1858.94
   350.8 1849.74   390.2 1828.36   398.2 1825.01   403.3 1823.76   409.8 1823.37
     423 1824.35   439.3 1825.62   445.9 1827.58   465.5 1838.67   501.6 1856.01
   531.1 1872.23   540.9    1876   570.4 1884.19   593.3 1894.48   652.3 1925.64
   681.8 1939.35   704.7 1953.66     744 1967.04   757.2 1970.79     767 1975.04
#Mann= 4, -1 ,  0
       0   0.035       0      70     0.1       0   398.2   0.045       0
     423     0.1       0
Bank Sta=398.2,423
XS Rating Curve= 0 ,0
Exp/Cntr=0.3,0.1

Type RM Length L Ch R = 1 ,14422   ,238.8,240.4,240.6
XS GIS Cut Line= 2
     2085851.881       237181.84     2086588.683      237281.433
#Sta/Elev= 30
       0 1970.17      36 1961.63    49.1 1956.82    85.2 1945.88   114.6 1936.08
   153.9 1925.64   186.7  1913.9   219.4 1900.55   258.8 1887.41   268.6  1882.2
   294.8 1862.19   350.5 1825.81   360.3 1820.38   373.4  1815.3   380.1 1811.07
   383.2 1809.38   389.8 1808.67   399.6 1810.14   406.1 1812.07   412.7 1815.23
   448.7 1840.01   491.3 1863.69     524 1878.23   533.9 1880.82   560.1 1890.87
   602.7 1905.03   632.1 1911.27   661.6  1913.7   707.5 1912.42   743.5 1909.21
#Mann= 4, -1 ,  0
       0   0.035       0      60     0.1       0   380.1   0.045       0
   399.6     0.1       0
Bank Sta=380.1,399.6
XS Rating Curve= 0 ,0
Exp/Cntr=0.3,0.1

Type RM Length L Ch R = 1 ,14181   ,240.8,238,227.7
XS GIS Cut Line= 2
     2085804.601      237381.981     2086536.573      237527.771
#Sta/Elev= 30
       0 1971.32    65.5 1951.99   183.3 1909.62   235.7 1876.74   248.8 1865.01
   271.7 1849.53   294.6  1832.2   307.7 1825.51   333.9 1817.55     355 1805.11
   366.6 1803.68   376.4 1804.57   399.4 1806.26   412.5 1810.48   445.2 1829.98
   471.4 1847.92   484.5 1858.08   507.4  1870.5   513.9 1872.86   523.8 1874.33
   536.8 1873.62   576.1 1866.96   592.5 1861.97   615.4 1849.75   631.8 1847.81
   638.3 1849.53   651.4 1857.74   687.4 1874.32   723.4 1888.39   746.4 1895.97
#Mann= 4, -1 ,  0
       0   0.035       0      10     0.1       0     355   0.045       0
   376.4     0.1       0
Bank Sta=355,376.4
XS Rating Curve= 0 ,0
Exp/Cntr=0.3,0.1

Type RM Length L Ch R = 1 ,13943   ,242.5,250,257.2
XS GIS Cut Line= 3
     2085782.257      237707.445     2086146.381       237682.71
     2086509.705      237653.966
#Sta/Elev= 30
       0  1948.5    26.1 1944.29    42.4 1940.63    71.7 1931.78   136.9 1907.99
   159.7 1898.67   179.2 1889.05   221.6 1872.67   244.4 1858.15   260.7 1844.18
   296.5 1821.11   335.6  1800.8   357.5 1795.74   371.5 1795.19   381.2  1796.1
   387.7 1797.29   413.8 1798.66     430 1806.67   436.6    1808   469.1 1810.25
   491.9 1813.33   514.6 1812.99   524.4  1814.5   537.4  1820.7   566.7 1831.97
   631.8 1853.92   648.1 1861.54   664.3 1870.88   693.6 1885.43   729.4 1899.38
#Mann= 4, -1 ,  0
       0   0.035       0     100     0.1       0   357.5   0.045       0
   381.2     0.1       0
Bank Sta=357.5,381.2
XS Rating Curve= 0 ,0
Exp/Cntr=0.3,0.1

Type RM Length L Ch R = 1 ,13693   ,254.5,249.1,241.8
XS GIS Cut Line= 3
     2085776.192      237816.488     2086130.033      237920.459
     2086479.361      238038.944
#Sta/Elev= 30
       0 1934.25    19.6 1931.96    42.4 1928.38    91.4  1914.7   143.6 1895.72
     173 1884.24   192.6 1875.21   205.6 1867.39   231.7 1854.85     235 1852.49
   241.5 1846.44   251.3 1840.07   283.9  1822.3   306.8 1811.81   319.8 1804.01
   329.6 1799.22   342.7 1791.02     359 1785.74   368.8 1785.07   378.6 1785.85
   385.1 1786.85   391.6 1789.06   417.8 1804.63   505.9 1853.67     532 1865.83
   571.2 1879.69   616.9 1892.41   698.5 1911.74   711.6 1916.26   737.7 1921.89
#Mann= 4, -1 ,  0
       0   0.035       0      40     0.1       0     359   0.045       0
   378.6     0.1       0
Bank Sta=359,378.6
XS Rating Curve= 0 ,0
Exp/Cntr=0.3,0.1