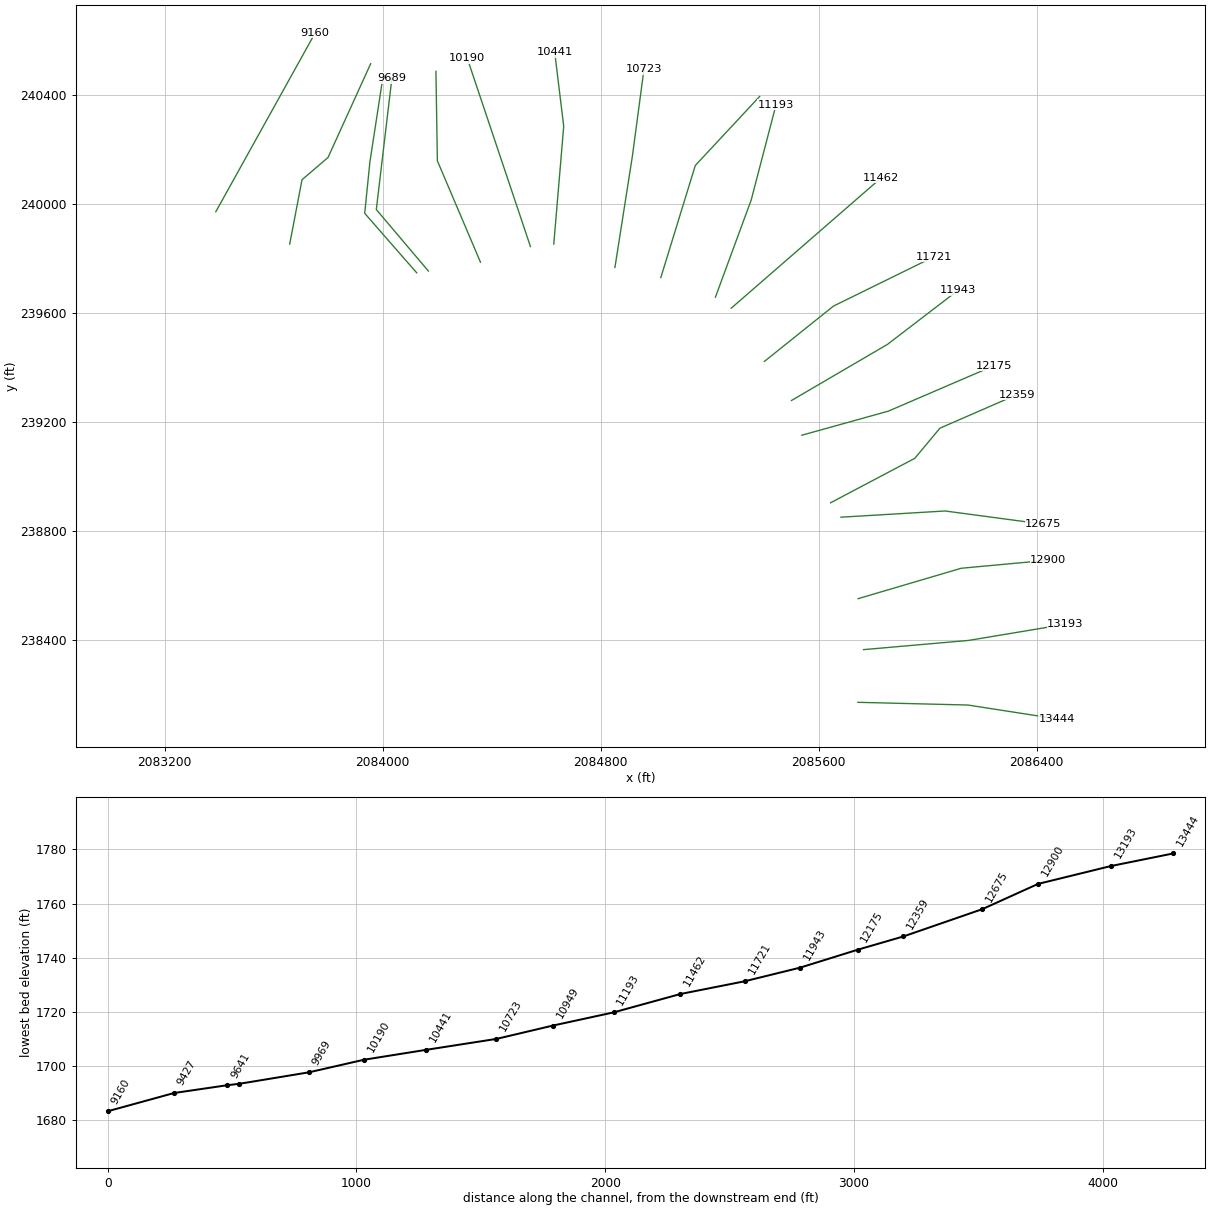
HEC-RAS study BROADRUN.prj: BROADRUN

--- BROADRUN.g01 (geometry) --- (continued)

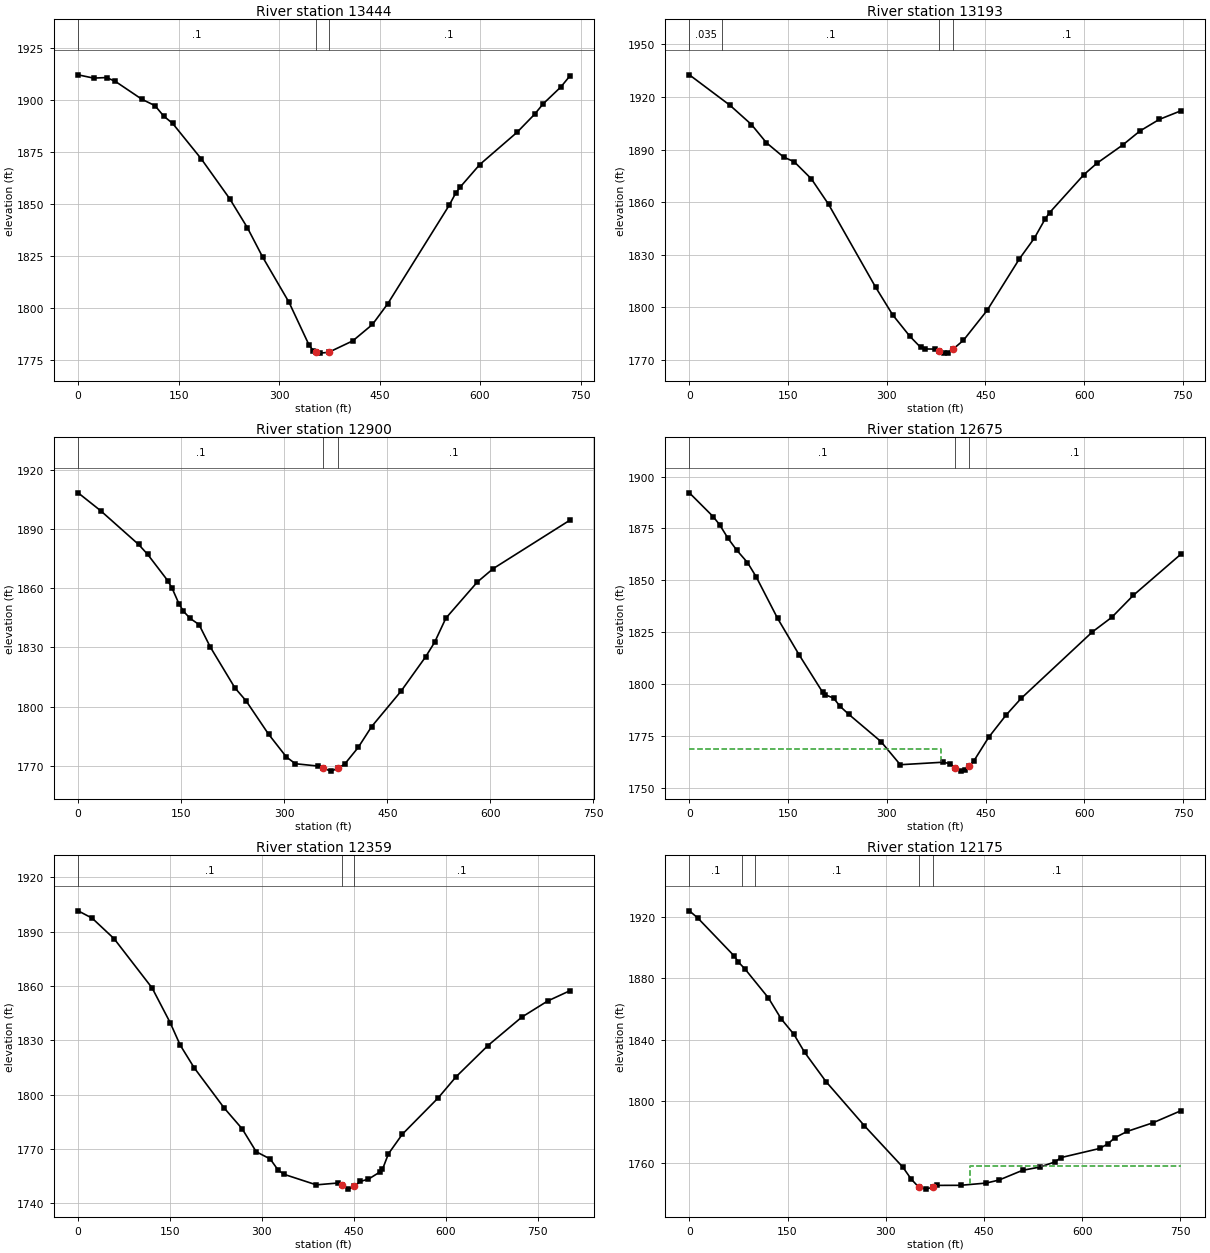
Type RM Length L Ch R = 1 ,13444   ,248,250.9,254.1
XS GIS Cut Line= 3
     2085743.839      238172.602     2086147.136      238162.671
     2086473.473      238111.999
#Sta/Elev= 30
       0 1912.22      23 1910.65    42.6 1910.91    55.8 1909.02    95.1  1900.5
   114.8  1897.4   127.9 1892.36     141 1888.92   183.7 1871.91   226.3  1852.7
   252.6 1838.84   275.5 1824.68   314.9 1802.92   344.4 1782.66   350.9 1779.73
   355.3 1778.97   360.8 1778.54   373.9 1778.91     410 1784.43   439.4 1792.31
   462.3 1802.29   553.8 1849.47   563.6 1855.34   570.2 1858.23   599.6 1869.12
   655.2 1884.59   681.4 1893.25   694.4 1898.34   720.6 1906.36   733.7 1911.51
#Mann= 3, -1 ,  0
       0     0.1       0   355.3   0.045       0   373.9     0.1       0
Bank Sta=355.3,373.9
XS Rating Curve= 0 ,0
Exp/Cntr=0.3,0.1

Type RM Length L Ch R = 1 ,13193   ,287.3,293.5,288.9
XS GIS Cut Line= 3
     2085764.273      238365.915     2086149.944      238399.673
     2086504.962      238458.843
#Sta/Elev= 30
       0 1932.66    61.8 1915.26    94.4 1904.29   117.1 1893.92   143.2 1885.75
   159.4 1883.05   185.4 1873.32   211.5 1858.83     283 1811.58   309.1 1795.69
   335.1 1783.52   351.4 1777.22   357.9 1776.26   374.1 1776.18   379.6 1775.09
   387.2 1773.88   393.7 1774.22   400.2 1775.97   416.6 1781.19   452.6 1798.26
   501.7 1827.68   524.6 1839.58   540.9 1850.49   547.5    1854   599.8 1875.74
   619.4 1882.18   658.7 1892.62   684.9 1900.61   714.3 1907.22   747.1 1912.12
#Mann= 4, -1 ,  0
       0   0.035       0      50     0.1       0   379.6   0.045       0
   400.2     0.1       0
Bank Sta=379.6,400.2
XS Rating Curve= 0 ,0
Exp/Cntr=0.3,0.1

Type RM Length L Ch R = 1 ,12900   ,231.4,224.6,213.4
XS GIS Cut Line= 3
     2085744.451      238552.827     2086122.831      238664.407
     2086442.275      238693.921
#Sta/Elev= 30
       0  1908.3    32.6 1899.29      88 1882.14   101.1 1877.16   130.4 1863.81
   136.9 1859.88   146.7 1852.11   153.2 1848.32     163 1844.67     176 1841.53
   192.4 1830.14   228.2 1809.46   244.5 1802.85   277.1 1786.02   303.2  1774.4
   316.2 1771.01   348.8 1769.84   355.8 1768.77   368.4 1767.26   378.2  1768.7
     388 1770.83   407.6 1779.24   427.2 1789.84   469.8 1807.69   505.8  1825.2
   518.9 1832.58   535.2 1844.76   581.1 1863.12     604 1869.86   715.3 1894.33
#Mann= 3, -1 ,  0
       0     0.1       0   355.8   0.045       0   378.2     0.1       0
Bank Sta=355.8,378.2
XS Rating Curve= 0 ,0
Exp/Cntr=0.3,0.1

Type RM Length L Ch R = 1 ,12675   ,296.6,316.7,336.3
XS GIS Cut Line= 3
     2085681.683      238851.737     2086063.544      238874.514
     2086424.423      238826.259
#Sta/Elev= 30
       0 1892.19      36 1880.75    45.8 1876.88    58.8 1870.19    71.9 1864.55
    88.3 1858.55   101.4 1851.72     134 1831.63   166.8 1813.98   202.7 1795.85
     206 1794.81   219.1 1793.14   228.9 1789.19     242 1785.36     291 1772.19
   320.4    1761   385.8 1762.22   395.7 1761.48   403.9 1759.53   412.1 1757.91
   418.6 1758.66   425.2 1760.42   431.7  1762.6   454.7 1774.24   480.9 1784.88
   503.9 1792.98   612.2 1825.08   641.7 1832.13   674.5 1842.76   746.6 1862.57
#Mann= 3, -1 ,  0
       0     0.1       0   403.9   0.045       0   425.2     0.1       0
#XS Ineff= 2 , 0
          382.81 1768.61
Permanent Ineff=
       F       F
Bank Sta=403.9,425.2
XS Rating Curve= 0 ,0
Exp/Cntr=0.3,0.1

Type RM Length L Ch R = 1 ,12359   ,191.1,183.5,172.3
XS GIS Cut Line= 4
     2085643.344      238904.507     2085952.372      239067.701
     2086044.706      239178.296     2086327.692       239301.56
#Sta/Elev= 30
       0 1901.52    22.9 1897.47    58.8  1886.1   120.8 1858.91   150.2 1839.81
   166.6 1827.39   189.4 1814.87   238.4 1792.64   267.8 1781.13   290.7 1768.48
   313.5  1764.5   326.6 1758.29   336.4 1755.99   388.8  1750.2   424.8 1751.24
   431.3 1750.06   441.2 1747.84     451 1749.43   460.8 1752.12   473.9 1753.36
   493.5 1757.48   496.8 1758.76   506.5 1767.35   529.3 1778.19   587.8 1798.25
     617 1809.92     669 1827.14   724.2 1842.82   766.5 1851.74   802.2 1857.31
#Mann= 3, -1 ,  0
       0     0.1       0   431.3   0.045       0     451     0.1       0
Bank Sta=431.3,451
XS Rating Curve= 0 ,0
Exp/Cntr=0.3,0.1

Type RM Length L Ch R = 1 ,12175   ,228.3,232.3,234.3
XS GIS Cut Line= 3
     2085538.161      239152.483     2085855.469      239240.796
     2086242.622      239407.463
#Sta/Elev= 30
       0 1923.77      13 1919.04    68.5 1894.42      75 1890.42    84.8 1886.06
   120.7 1867.23   140.2 1853.61   159.8 1843.47   176.1 1831.81   208.7 1812.83
   267.4 1784.12   326.1 1757.25   339.2 1749.29   350.5 1744.23     362 1742.94
   371.8 1744.27   378.4 1745.37   414.3 1745.42   453.5 1746.88   473.1 1748.84
   509.1 1755.17   535.2 1757.25   558.1 1760.54   567.9 1763.45   626.7 1769.34
   639.8 1772.44   649.6 1776.24   669.2 1780.49   708.4 1786.07   750.9 1793.86
#Mann= 5, -1 ,  0
       0     0.1       0      80   0.035       0     100     0.1       0
   350.5   0.045       0   371.8     0.1       0
#XS Ineff= 2 , 0
                          428.65         1758.15
Permanent Ineff=
       F       F
Bank Sta=350.5,371.8
XS Rating Curve= 0 ,0
Exp/Cntr=0.3,0.1

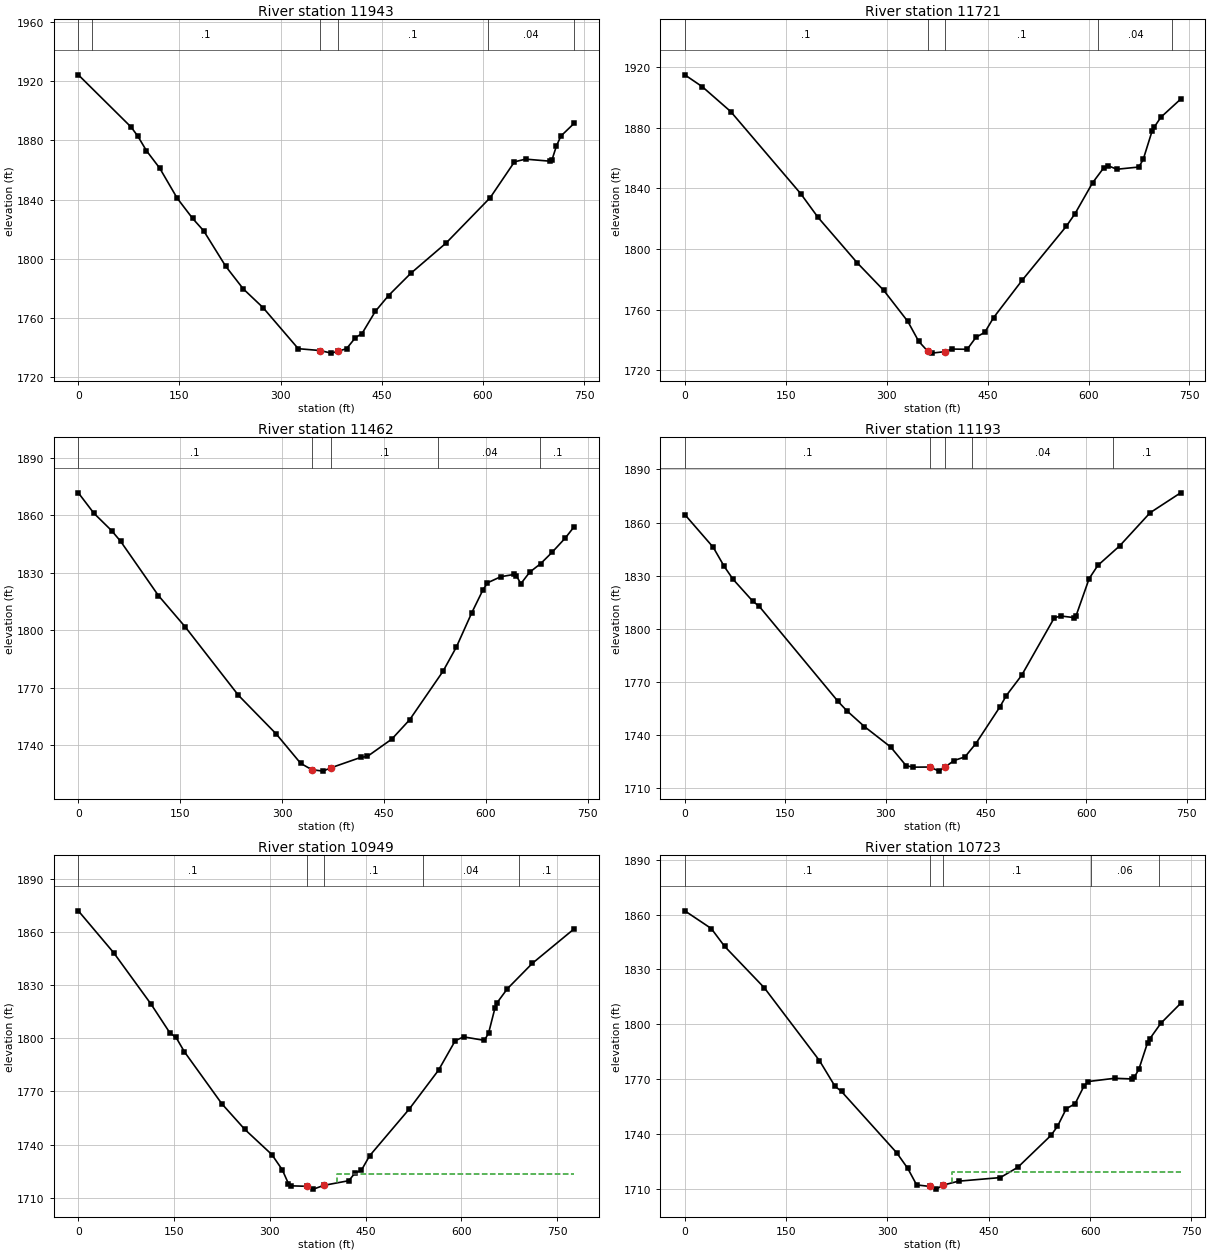
Type RM Length L Ch R = 1 ,11943   ,222.6,221.7,219.2
XS GIS Cut Line= 3
     2085500.034      239279.842     2085851.997      239485.588
     2086112.168      239684.912
#Sta/Elev= 30
       0 1924.28    78.3 1888.98    88.1 1882.92   101.1 1872.98   120.7 1861.23
   146.8 1840.84   169.6 1827.24   185.9 1818.92   218.5 1795.03   244.6  1779.7
     274 1767.01   326.2 1739.29   358.8 1738.03   375.1 1736.29   384.9 1737.48
   397.9 1739.33     411 1746.74   420.8 1749.53   440.5 1764.49   460.1 1775.18
   492.9 1790.11   545.3 1810.58   610.9 1841.29   646.9  1865.5   663.3 1867.33
   699.4 1865.95   702.7 1867.05   709.2 1876.28   715.8 1882.93   735.4 1891.52
#Mann= 6, -1 ,  0
       0   0.035       0      20     0.1       0   358.8   0.045       0
   384.9     0.1       0  607.69    0.04       0  735.44     0.1       0
Bank Sta=358.8,384.9
XS Rating Curve= 0 ,0
Exp/Cntr=0.3,0.1

Type RM Length L Ch R = 1 ,11721   ,251.3,259.4,264
XS GIS Cut Line= 3
     2085400.608      239423.088     2085654.081      239626.213
     2086024.029      239807.827
#Sta/Elev= 30
       0  1914.8      26 1906.96    68.2 1890.59   172.2 1836.47   198.1 1820.74
   256.6 1790.67   295.6 1772.69   331.4 1752.21   347.7 1739.01   360.8 1732.68
   367.3 1731.28     387 1732.29   396.8 1733.97   419.7 1733.81   432.8 1741.75
   445.8 1744.98   458.9 1754.69   501.4 1779.35   566.9 1814.87   579.9  1823.2
   606.1 1843.64   622.5  1853.4     629 1854.88   642.1 1852.53   674.8    1854
   681.3    1859   694.4 1877.63   697.7 1880.33   707.5 1886.81   736.9 1898.76
#Mann= 5, -1 ,  0
       0     0.1       0   360.8   0.045       0     387     0.1       0
  614.82    0.04       0  724.82     0.1       0
Bank Sta=360.8,387
XS Rating Curve= 0 ,0
Exp/Cntr=0.3,0.1

Type RM Length L Ch R = 1 ,11462   ,253.9,268.3,278.9
XS GIS Cut Line= 2
     2085279.078       239618.51     2085829.854      240097.195
#Sta/Elev= 30
       0 1871.82    22.9 1861.16    49.1 1852.04    62.2 1846.53   117.8 1818.21
   157.1 1801.93   235.6 1766.14   291.2 1745.96   327.2 1730.62   343.6 1727.31
     360 1726.55   371.4 1728.24   415.6 1733.71   425.4 1734.23   461.4 1743.29
   487.6 1753.36   536.7 1778.68   556.3 1791.27   579.2 1809.35   595.6 1821.26
   602.1 1824.84   621.7 1828.03   641.4 1829.23   644.6  1828.6   651.2 1824.36
   664.3  1830.4   680.6 1834.91     697  1840.7   716.6 1848.21   729.7 1854.13
#Mann= 5, -1 ,  0
       0     0.1       0   343.6   0.045       0   371.4     0.1       0
     530    0.04       0     680     0.1       0
Bank Sta=343.6,371.4
XS Rating Curve= 0 ,0
Exp/Cntr=0.3,0.1

Type RM Length L Ch R = 1 ,11193   ,241.5,244,242.2
XS GIS Cut Line= 3
     2085221.062       239658.97     2085352.201       240015.15
     2085443.391      240364.706
#Sta/Elev= 30
       0 1864.51    42.5 1846.03    58.9 1835.25      72 1828.04   101.4 1815.69
   111.2 1812.73     229 1759.06   242.1 1753.83   268.3 1744.92   307.6 1733.36
   330.5 1722.91   340.3 1721.99   366.5 1722.08   379.6 1719.76   389.3 1722.18
   402.3 1725.74   418.6  1727.8   434.9 1735.32   470.7 1755.94   480.4 1762.41
   503.2 1773.76     552 1806.22   561.8 1807.29   581.3 1806.38   584.6 1807.42
   604.1 1828.36   617.1 1835.81   649.7 1846.83   695.2 1865.53   740.8 1876.77
#Mann= 5, -1 ,  0
       0     0.1       0   366.5   0.045       0   389.3     0.1       0
  429.55    0.04       0  639.55     0.1       0
Bank Sta=366.5,389.3
XS Rating Curve= 0 ,0
Exp/Cntr=0.3,0.1

Type RM Length L Ch R = 1 ,10949   ,223.7,226.8,229.9
XS GIS Cut Line= 3
     2085020.716       239730.74     2085147.136      240141.838
     2085383.247       240395.31
#Sta/Elev= 30
       0 1871.98    55.4 1848.31     114 1819.25   143.4 1803.08   153.1 1800.49
   166.2 1792.37   224.8 1763.04   260.7 1748.61     303 1734.42   319.3 1725.88
   329.1 1717.94   332.4 1716.76   358.4 1716.48   368.2 1714.89   384.5 1717.02
   423.6 1719.65   433.4 1724.03   443.2 1725.49   456.2 1733.72   518.3 1760.13
   564.1 1782.04   590.2 1798.64   603.3 1800.84     636 1798.85   642.5 1802.99
   652.3 1816.87   655.6 1820.02   671.9    1828   711.1 1842.37   776.5 1861.81
#Mann= 5, -1 ,  0
       0     0.1       0   358.4   0.045       0   384.5     0.1       0
   540.1    0.04       0   690.1     0.1       0
#XS Ineff= 2 , 0
                          405.41         1723.63
Permanent Ineff=
       F       F
Bank Sta=358.4,384.5
XS Rating Curve= 0 ,0
Exp/Cntr=0.3,0.1

Type RM Length L Ch R = 1 ,10723   ,279,282,283
XS GIS Cut Line= 3
     2084852.363      239768.008     2084916.233      240174.824
      2084958.79      240494.148
#Sta/Elev= 30
       0 1862.02    39.2 1852.34    58.8 1842.67   117.7 1819.97   199.4 1780.15
   222.2 1766.24     232 1763.31   313.8 1729.78   330.1 1721.26   343.2 1712.27
   363.4  1711.4   372.6 1709.96   382.4 1712.17   405.3  1714.3   467.1 1716.27
   493.2 1721.95     542  1739.3   551.7 1744.27   564.7 1753.89   577.8 1756.61
   590.8 1766.17   597.3 1768.75   636.3 1770.53   662.4 1770.16   665.6 1771.21
   672.1 1775.37   685.1 1790.03   688.4 1792.12   704.7 1800.56     734 1811.45
#Mann= 5, -1 ,  0
       0     0.1       0   363.4   0.045       0   382.4     0.1       0
   601.8    0.06       0   701.8     0.1       0
#XS Ineff= 2 , 0
                          395.32          1719.2
Permanent Ineff=
       F       F
Bank Sta=363.4,382.4
XS Rating Curve= 0 ,0
Exp/Cntr=0.3,0.1

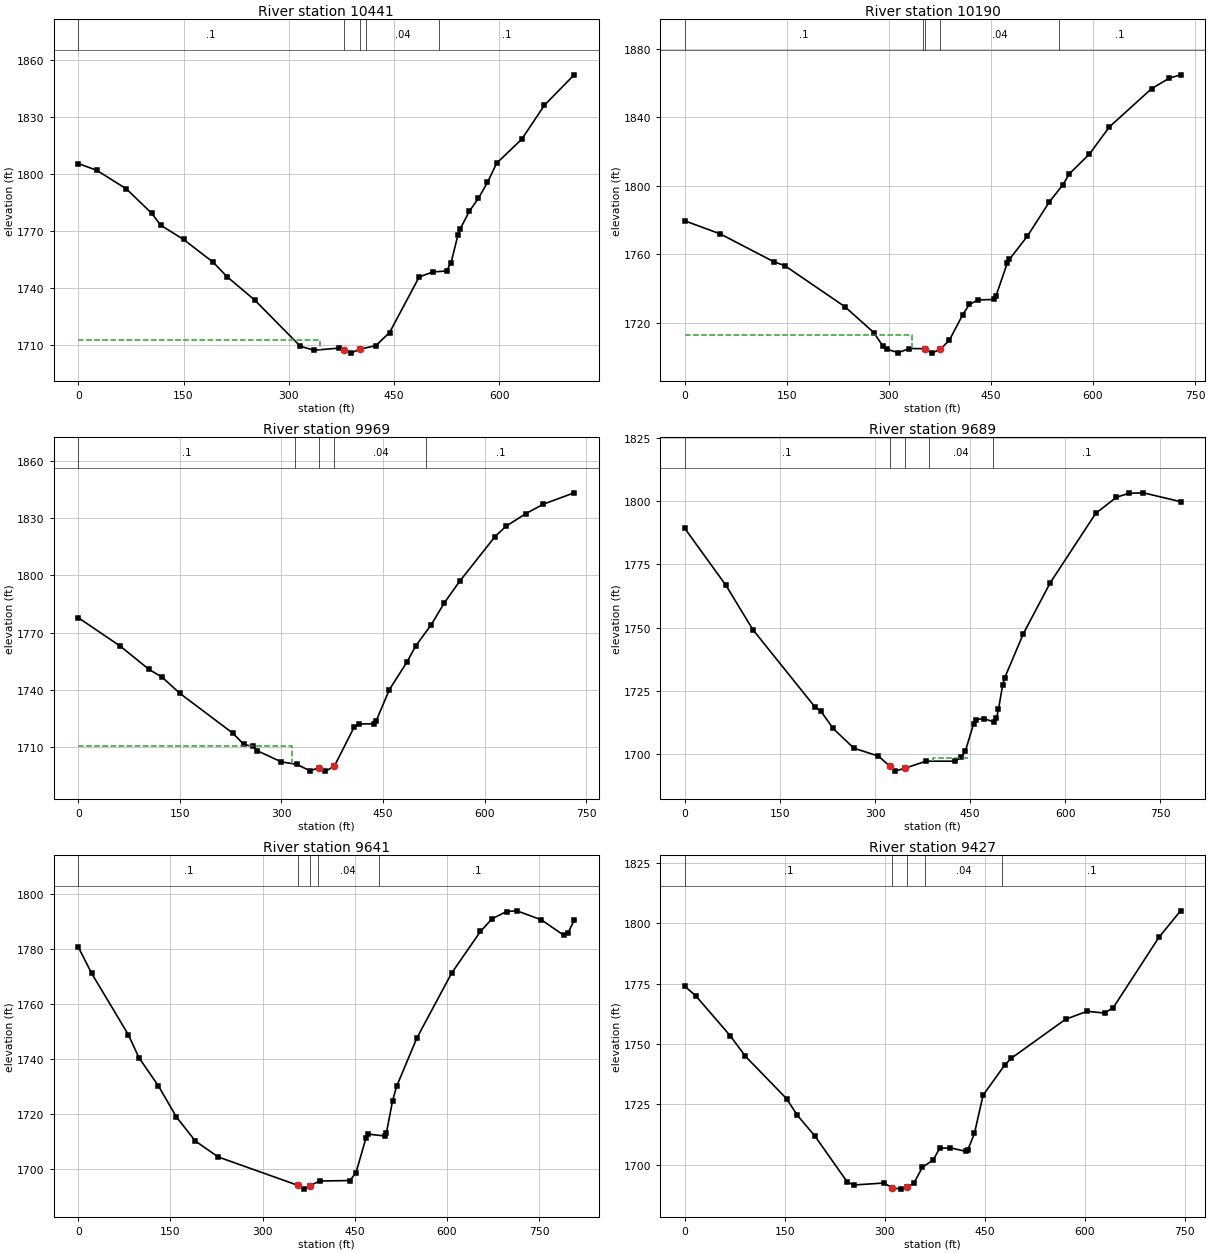
Type RM Length L Ch R = 1 ,10441   ,241.9,250.5,258.7
XS GIS Cut Line= 3
     2084628.039      239853.644     2084664.497      240285.935
     2084631.511      240556.769
#Sta/Elev= 30
       0 1805.47    26.1 1801.95    68.5 1792.17   104.4 1779.41   117.4  1773.1
     150 1765.61   192.4 1753.59     212 1746.04   251.2 1733.87   316.4 1709.55
     336 1707.44   371.8 1708.58   378.4 1707.53   388.2 1705.93   401.2 1707.97
     424 1709.86   443.6 1716.72   485.8 1745.92   505.3 1748.55   524.8 1749.06
   531.3 1753.41     541 1767.89   544.3 1771.12   557.2 1780.36   570.2 1787.18
   583.2 1795.57   596.2 1805.65     632 1818.25   664.4 1836.12   706.7 1852.06
#Mann= 5, -1 ,  0
       0     0.1       0   378.4   0.045       0   401.2     0.1       0
     410    0.04       0  513.83     0.1       0
#XS Ineff= 2 , 0
          344.86 1712.82
Permanent Ineff=
       F       F
Bank Sta=378.4,401.2
XS Rating Curve= 0 ,0
Exp/Cntr=0.3,0.1

Type RM Length L Ch R = 1 ,10190   ,219.6,221.4,223
XS GIS Cut Line= 2
     2084542.446      239844.559     2084310.596      240535.427
#Sta/Elev= 30
       0 1779.53    52.3 1771.87   130.7 1755.66     147 1753.36   235.3 1729.38
   277.8 1714.27   290.8 1706.55   297.4 1704.47   313.7 1702.54     330 1704.94
   352.9 1704.86   362.7 1702.26   375.8 1704.56   388.9 1709.84   408.5 1724.69
   418.3 1730.76   431.4 1733.33   454.2  1733.6   457.5 1735.79   473.8 1754.65
   477.1 1757.03   503.2 1770.39   535.9 1790.63   555.5  1800.5   565.3 1807.04
   594.8 1818.58   624.2 1834.44   686.2 1856.79   712.4 1862.91   728.7 1864.82
#Mann= 5, -1 ,  0
       0     0.1       0     350    0.04       0   352.9   0.045       0
   375.8    0.04       0     550     0.1       0
#XS Ineff= 2 , 0
          333.52 1712.72
Permanent Ineff=
       F       F
Bank Sta=352.9,375.8
XS Rating Curve= 0 ,0
Exp/Cntr=0.3,0.1

Type RM Length L Ch R = 1 ,9969    ,286.5,280.1,264.8
XS GIS Cut Line= 3
     2084359.064      239787.228     2084200.956      240159.199
     2084195.747      240487.324
#Sta/Elev= 30
       0 1777.85    61.9 1762.99   104.3 1750.84   123.9 1746.72   149.9  1738.3
   228.2 1717.46   244.5 1711.55   257.5  1710.6     264 1708.31   299.9 1702.44
   322.7 1701.16   342.2 1697.77   355.3 1699.36   365.1 1697.61   378.1 1700.12
   407.4 1720.63   413.9 1722.29   436.7 1722.34   439.9 1723.84   459.4 1740.19
   485.4 1754.65   498.4 1763.12   521.2  1774.1   540.6 1785.62   563.4 1796.95
   615.4 1820.23   631.6 1825.64   660.9 1832.27   686.9 1837.24   732.4 1843.17
#Mann= 5, -1 ,  0
       0     0.1       0     320    0.04       0   355.3   0.045       0
   378.1    0.04       0  514.18     0.1       0
#XS Ineff= 2 , 0
          316.33 1710.99
Permanent Ineff=
       F       F
Bank Sta=355.3,378.1
XS Rating Curve= 0 ,0
Exp/Cntr=0.5,0.3

Type RM Length L Ch R = 1 ,9689    ,46.9,47.5,47.2
XS GIS Cut Line= 3
     2084167.969      239754.685     2083976.997       239980.38
     2084034.289      240463.019
#Sta/Elev= 30
       0 1789.22      65 1766.69   107.2 1749.28   204.7 1718.85   214.4 1717.09
   233.9 1710.22   266.4 1702.44   305.4 1699.29     323 1695.34   331.5 1693.36
   347.8 1694.58   380.5 1697.29   426.1 1697.28   435.9 1698.84   442.4 1701.32
   455.5 1712.14   458.8  1713.7   471.8 1714.11   488.1  1712.7   491.4 1714.36
   494.6 1717.77   501.2 1727.42   504.4 1730.22   533.8 1747.63   576.2 1767.74
   647.9 1795.15   680.6 1801.53   700.1 1803.06     723 1803.26   781.7 1799.77
#Mann= 5, -1 ,  0
       0     0.1       0     323   0.045       0   347.8     0.1       0
  385.65    0.04       0  485.65     0.1       0
#XS Ineff= 3 ,-1
       0  316.86 1695.48  362.85  381.04 1695.55  390.65   448.3  1698.7
Permanent Ineff=
       F       F       F
Bank Sta=323,347.8
XS Rating Curve= 0 ,0
Exp/Cntr=0.5,0.3

Type RM Length L Ch R = 1 ,9641    ,226.7,214.5,195.4
XS GIS Cut Line= 4
2084125.16243639239748.2799606772083934.39500888239966.418366914
2083953.47175164240154.6975236282084003.23716751240479.002150392
#Sta/Elev= 30
       0 1780.76    21.6 1771.25    81.4 1748.95    98.7 1740.57   130.2  1730.4
   159.7 1719.05   190.6 1710.29   227.8 1704.53   358.11694.173   367.5 1692.85
   376.5 1694.03   392.6 1695.79     442 1695.97   451.9 1698.78   468.4 1711.51
   471.7 1712.84   498.5 1712.15   501.5 1713.24   511.5 1724.93   518.1 1730.17
   551.3 1747.84   607.7 1771.32   654.6 1786.45   673.5 1791.06   697.1 1793.69
     714 1793.94   753.8 1790.66   790.3 1785.06   796.9 1785.76   807.1 1790.51
#Mann= 5, -1 ,  0
       0     0.1       0   358.1   0.045       0   376.5     0.1       0
  389.79    0.04       0  489.03     0.1       0
#XS Ineff= 2 ,-1
  322.02   350.5 1694.15  384.67  405.55 1694.18
Permanent Ineff=
       F       F
Bank Sta=358.1,376.5
XS Rating Curve= 0 ,0
Exp/Cntr(USF)=0,0
Exp/Cntr=0.5,0.3

Type RM Length L Ch R = 1 ,9427    ,260.9,266.7,273.4
XS GIS Cut Line= 4
     2083659.289      239853.644     2083704.428      240089.755
     2083799.914      240171.352     2083956.164      240515.102
#Sta/Elev= 30
       0  1773.9    16.2 1770.08    68.2 1753.44      91 1744.94   152.7 1727.38
   168.9 1720.48   194.9 1712.04   243.6 1692.95   253.3 1691.67   298.4 1692.48
   311.2 1690.52   324.1 1689.96   333.8 1691.02   343.4 1692.31   356.3    1699
   372.5 1702.02   382.3 1706.84   398.5 1707.05   421.3  1705.6   424.6 1706.29
   434.4    1713   447.4 1728.85   479.9 1741.36   489.7 1744.15   571.1 1760.28
   603.6 1763.58   629.6 1762.84   642.7 1765.11     711 1794.16   743.6 1805.17
#Mann= 5, -1 ,  0
       0     0.1       0   311.2   0.045       0   333.8     0.1       0
  360.39    0.04       0  475.99     0.1       0
Bank Sta=311.2,333.8
XS Rating Curve= 0 ,0
Exp/Cntr=0.3,0.1

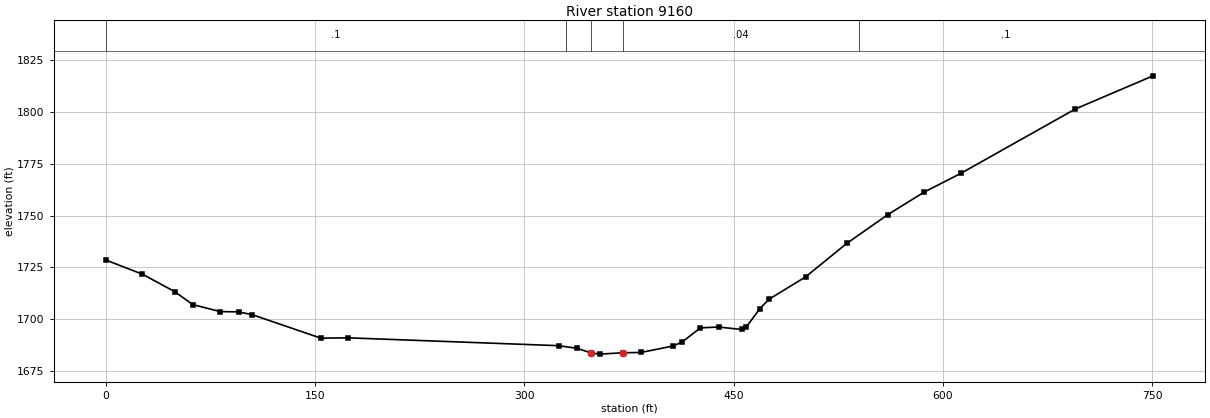
Type RM Length L Ch R = 1 ,9160    ,224.5,224.9,224.3
XS GIS Cut Line= 2
     2083388.136      239972.215     2083752.719      240628.465
#Sta/Elev= 30
       0 1728.56    26.2 1721.73    49.2 1713.38    62.3 1707.09      82 1703.72
    95.1 1703.58   104.9 1702.23   154.1 1690.92   173.8 1691.07   324.6 1687.29
   337.7 1686.03   347.5 1683.88     354 1683.22   370.4 1683.87   383.6 1684.03
   406.5 1687.11   413.1 1689.06   426.2 1695.88   439.3 1696.28   455.7  1695.1
     459  1696.2   468.8 1705.14   475.4 1709.68   501.6 1720.44   531.1 1736.57
   560.6 1750.48   586.8 1761.37     613 1770.37     695 1801.36   750.7 1817.34
#Mann= 5, -1 ,  0
       0     0.1       0     330    0.04       0   347.5   0.045       0
   370.4    0.04       0     540     0.1       0
Bank Sta=347.5,370.4
XS Rating Curve= 0 ,0
Exp/Cntr=0.3,0.1