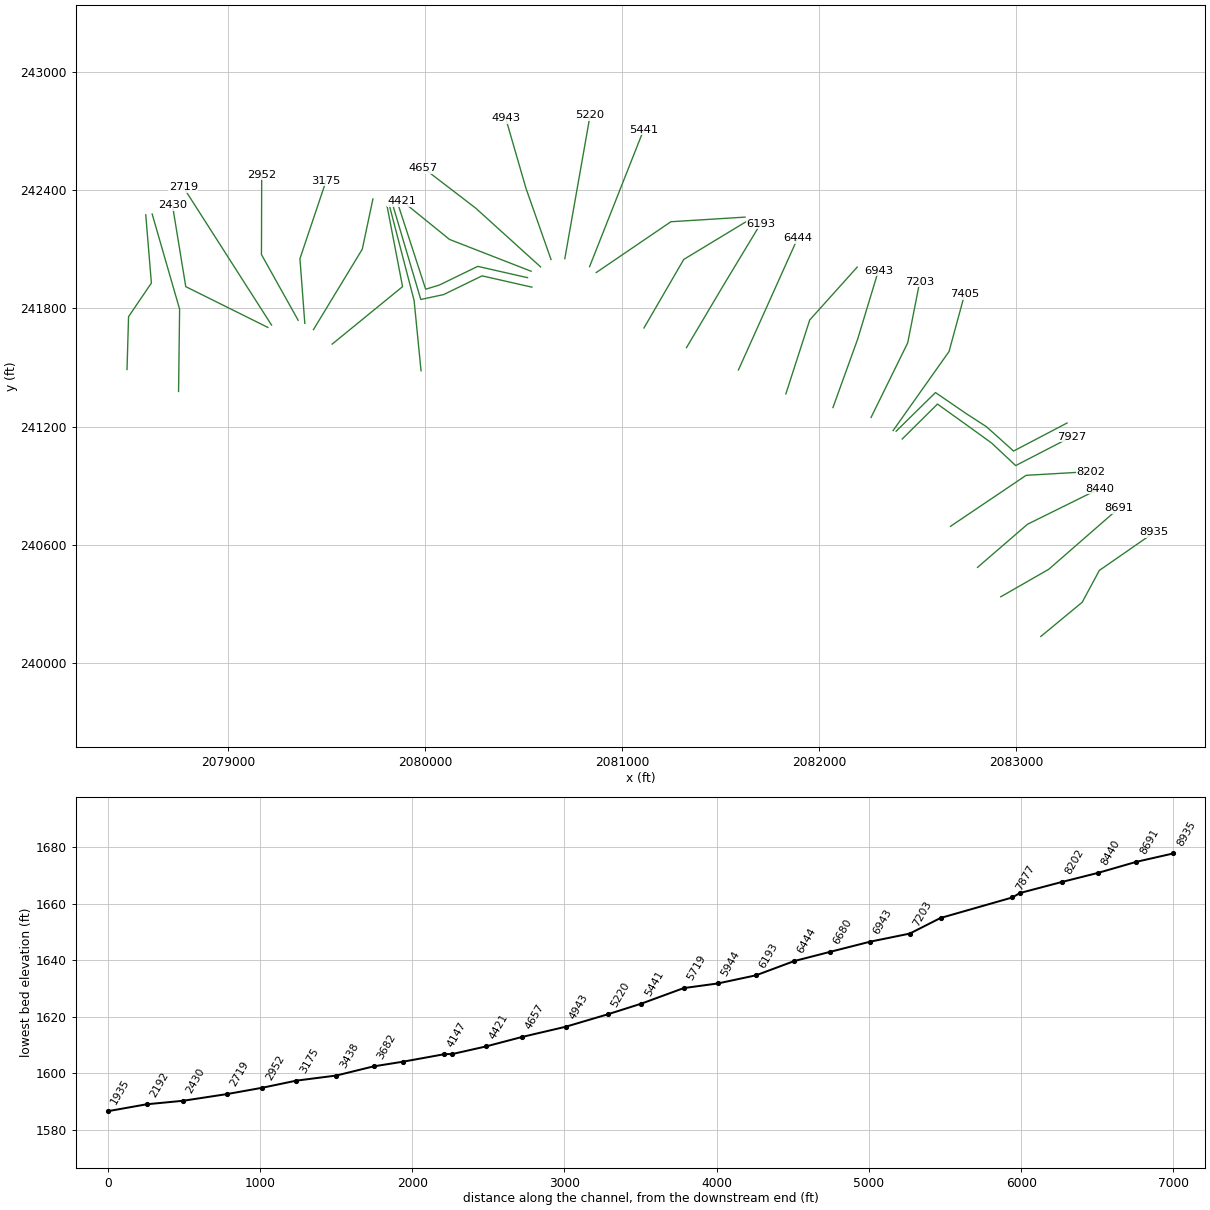
HEC-RAS study BROADRUN.prj: BROADRUN

--- BROADRUN.g01 (geometry) --- (continued)

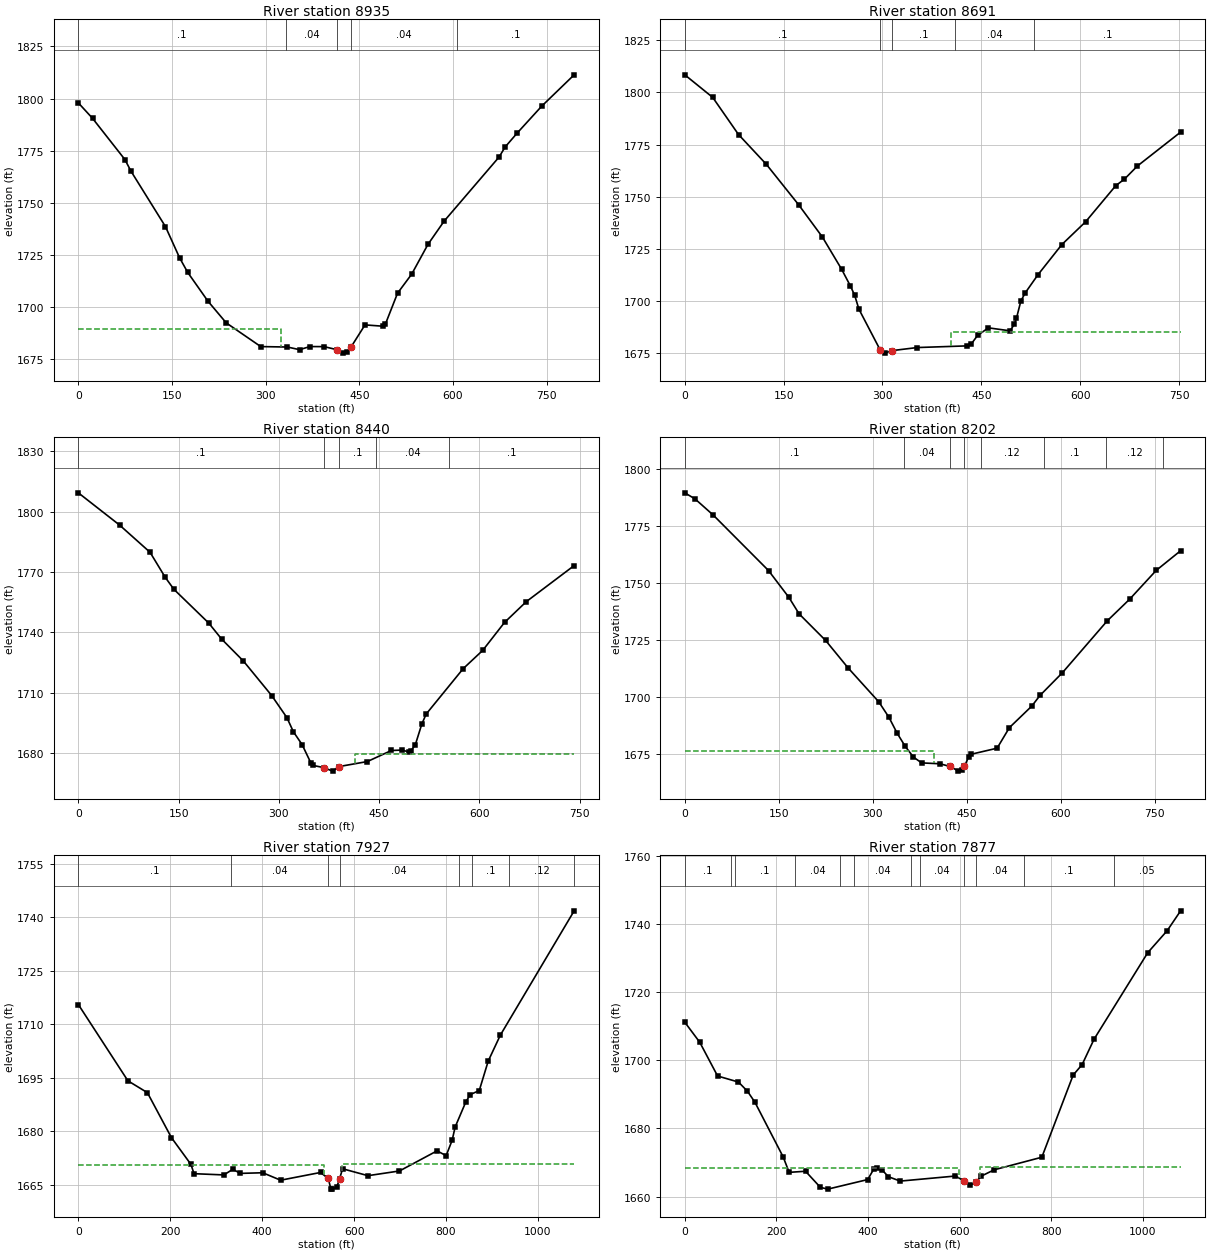
Type RM Length L Ch R = 1 ,8935    ,249.6,243.5,236.3
XS GIS Cut Line= 4
     2083126.303      240134.894     2083336.282      240308.553
     2083423.178      240469.963     2083700.956      240662.671
#Sta/Elev= 30
       0 1797.92    22.7 1790.52    74.6  1770.7    84.3 1765.12   139.5 1738.51
   162.2 1723.49   175.2 1716.49   207.6 1702.68   236.8 1692.29   292.1  1680.9
   334.7 1680.69   354.3 1679.42   370.7 1680.91   393.6 1680.88   413.6 1679.44
   423.1 1677.76   429.6 1678.26   436.2 1680.47     459 1691.32   488.3 1690.67
   491.6 1691.64   511.1 1706.53   533.8  1715.7   559.8 1729.97   585.8 1741.18
   673.6 1771.89   683.4 1776.74   702.9 1783.51   741.9 1796.33   793.9 1811.39
#Mann= 5, -1 ,  0
       0     0.1       0  332.49    0.04       0   413.6   0.045       0
   436.2    0.04       0   605.8     0.1       0
#XS Ineff= 2 , 0
          324.36 1689.57
Permanent Ineff=
       F       F
Bank Sta=413.6,436.2
XS Rating Curve= 0 ,0
Exp/Cntr=0.3,0.1

Type RM Length L Ch R = 1 ,8691    ,256.1,251.4,247.2
XS GIS Cut Line= 3
     2082923.178      240336.282     2083166.522      240475.799
     2083522.136      240785.935
#Sta/Elev= 30
       0 1808.49    42.4 1797.63    81.5 1779.81   123.9 1765.43   172.9    1746
   208.8 1730.56   238.1 1715.01   251.2  1707.1   257.7 1702.64   264.2 1695.91
   296.9 1676.06   303.4 1674.78   314.1 1675.97   352.6 1677.46     428 1678.26
   434.5 1679.07   444.3 1683.29   460.7 1686.93   493.5  1685.5     500 1688.57
   503.3 1691.54   509.9 1699.76   516.4 1703.64   536.1 1712.52   572.1 1726.92
   608.2 1737.88     654 1755.25   667.2 1758.39   686.8 1764.68   752.4 1780.97
#Mann= 5, -1 ,  0
       0     0.1       0   296.9   0.045       0   314.1     0.1       0
   410.5    0.04       0   530.5     0.1       0
#XS Ineff= 2 , 0
                          403.44         1685.04
Permanent Ineff=
       F       F
Bank Sta=296.9,314.1
XS Rating Curve= 0 ,0
Exp/Cntr=0.3,0.1

Type RM Length L Ch R = 1 ,8440    ,233.1,238.5,238.7
XS GIS Cut Line= 3
     2082805.122      240485.588     2083058.594      240704.338
     2083423.554      240884.767
#Sta/Elev= 30
       0 1809.38    61.8 1793.31   107.3 1779.79     130 1767.34     143 1761.36
     195  1744.6   214.5 1736.56     247 1725.66   289.3 1708.49   312.1 1697.49
   321.8 1690.45   334.8 1684.09   347.8 1675.04   351.1 1673.72   367.4 1672.61
   380.4 1670.87   390.2 1673.15   432.5 1675.64   468.4 1681.14   484.6 1681.36
   494.4  1680.4   497.7 1681.04   504.2 1683.96     514 1694.36   520.5 1699.29
   575.8 1721.85   605.1 1730.97   637.7 1744.87   670.3 1755.22   741.9 1773.17
#Mann= 5, -1 ,  0
       0     0.1       0   367.4   0.045       0   390.2     0.1       0
  444.81    0.04       0  554.81     0.1       0
#XS Ineff= 2 , 0
                          413.75         1679.48
Permanent Ineff=
       F       F
Bank Sta=367.4,390.2
XS Rating Curve= 0 ,0
Exp/Cntr=0.3,0.1

Type RM Length L Ch R = 1 ,8202    ,303,275,139.5
XS GIS Cut Line= 3
     2082667.969      240693.921      2083051.65      240952.602
     2083379.775      240971.699
#Sta/Elev= 30
       0 1789.65    16.3 1786.99    45.6 1779.84   133.6 1755.58   166.2 1743.79
   182.5 1736.57   224.8 1724.92   260.7 1712.87   309.6 1698.02   325.9 1691.21
   338.9 1684.28   351.9 1678.46     365 1673.78     378 1671.25   407.3 1670.86
   423.6 1669.67   436.7 1667.64   443.2 1668.32   446.4 1669.71     453  1673.9
   456.2 1674.98   498.5  1677.7   518.1 1686.71   553.9 1696.17   566.9 1700.81
   602.7 1710.78   674.3 1733.53   710.1 1743.03   752.4 1755.63   791.4 1764.27
#Mann= 8, -1 ,  0
       0     0.1       0     350    0.04       0   423.6   0.045       0
   446.4    0.04       0  472.74    0.12       0  572.74     0.1       0
  672.74    0.12       0  762.74     0.1       0
#XS Ineff= 2 , 0
          397.57 1676.49
Permanent Ineff=
       F       F
Bank Sta=423.6,446.4
XS Rating Curve= 0 ,0
Exp/Cntr=0.5,0.3

Type RM Length L Ch R = 1 ,7927    ,239.8,49.3,214.5
XS GIS Cut Line= 6
     2082422.858      241137.146     2082601.678      241314.229
     2082770.834      241193.053     2082877.171      241116.013
     2082998.699      241002.081     2083284.072       241149.65
#Sta/Elev= 30
       0 1715.48   107.9 1694.09   150.3 1690.77   202.6 1678.16   245.1 1670.65
   251.7 1668.06   316.7 1667.71   336.2  1669.3   352.4 1668.14   401.2 1668.32
   440.2 1666.23     527  1668.4  543.71 1666.72   549.4 1663.89   552.6 1663.73
   562.2 1664.22   568.6  1666.7     575 1669.44   630.2  1667.5   698.8 1668.82
   780.6 1674.46   800.3 1673.11   813.4 1677.42   819.9 1681.13   842.9  1688.1
   852.7 1690.22   872.4 1691.37     892 1699.66   918.3  1706.9  1078.9 1741.74
#Mann= 8, -1 ,  0
       0     0.1       0  331.66    0.04       0  543.71   0.045       0
   568.6    0.04       0  827.64    0.12       0  857.64     0.1       0
  937.64    0.12       0 1077.64    0.05       0
#XS Ineff= 2 , 0
           534.9  1670.6   573.7         1670.72
Permanent Ineff=
       F       F
Bank Sta=543.71,568.6
XS Rating Curve= 0 ,0
Exp/Cntr=0.5,0.3

Type RM Length L Ch R = 1 ,7877    ,224.1,472.1,532.7
XS GIS Cut Line= 6
     2082391.928       241176.56     2082591.581      241372.741
     2082751.303      241263.366     2082850.044      241199.564
     2082987.848      241075.866     2083259.115       241218.01
#Sta/Elev= 30
       0  1711.2    32.6 1705.32    71.6  1695.4   117.2 1693.62   136.7 1690.94
     153 1687.72   214.8 1671.62   227.8  1667.1   263.6 1667.42     296 1662.69
   312.2 1662.17   399.3 1664.98   412.2 1667.97   418.6 1668.33   431.6 1667.69
   444.4 1665.82   470.3 1664.53     591 1666.02   610.5 1664.52   623.5 1663.37
   636.5 1664.26   646.3 1665.93   675.5 1667.85   779.5 1671.54   847.9 1695.68
   867.4 1698.74   893.5 1706.21  1010.8 1731.64  1053.2  1738.1  1082.5 1743.92
#Mann= 12, -1 ,  0
       0     0.1       0     100    0.05       0     110     0.1       0
     240    0.04       0  339.91     0.1       0  369.91    0.04       0
  493.49     0.1       0  513.49    0.04       0   610.5   0.045       0
   636.5    0.04       0  741.05     0.1       0  936.23    0.05       0
#XS Ineff= 2 , 0
          598.76 1668.28  644.12         1668.77
Permanent Ineff=
       F       F
Bank Sta=610.5,636.5
XS Rating Curve= 0 ,0
Exp/Cntr=0.5,0.3

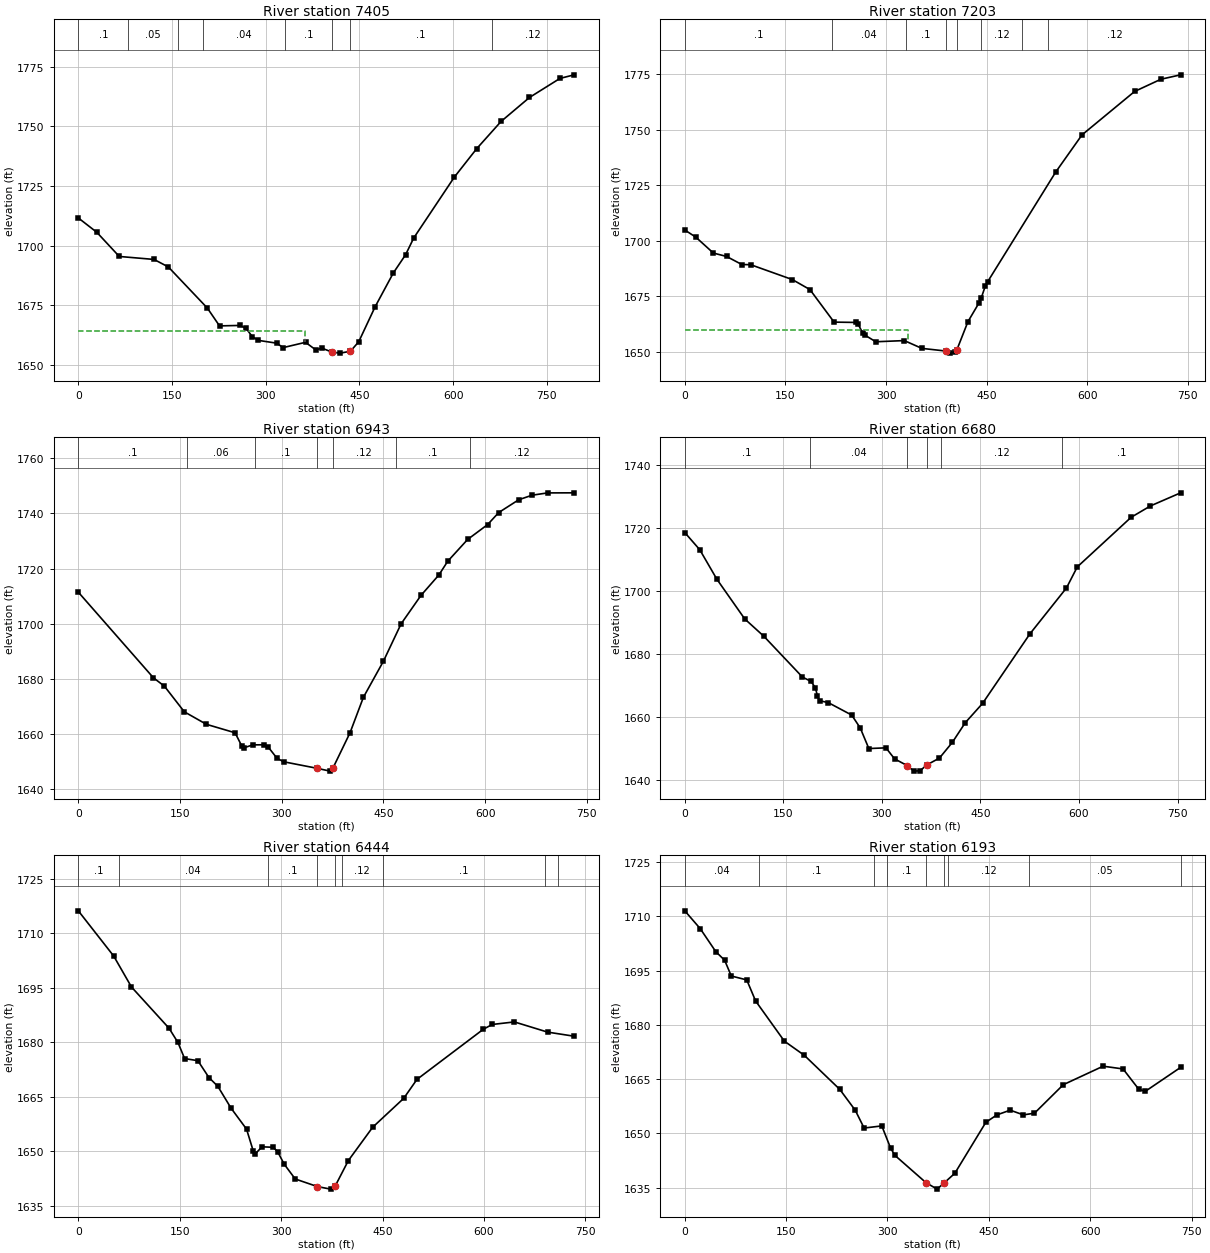
Type RM Length L Ch R = 1 ,7405    ,195,202.4,207.4
XS GIS Cut Line= 3
      2082376.52      241179.815     2082660.374      241580.857
     2082739.801      241872.524
#Sta/Elev= 30
       0 1711.57    29.5 1705.58    65.5 1695.43   121.2 1694.18   144.1 1691.02
   206.4 1673.82     226 1666.32   258.8 1666.51   268.6 1665.24   278.4 1661.83
   288.2 1660.24   317.7 1659.07   327.6  1657.2   363.6 1659.43     380 1656.27
   389.8    1657   406.2  1655.3   419.3  1654.9   435.6  1655.7   448.8 1659.67
     475 1674.32   504.3 1688.57   523.8 1696.15   536.8 1703.16   601.8 1728.69
   637.6 1740.62   676.6 1752.03   722.1 1762.09   770.9 1770.08   793.6 1771.58
#Mann= 8, -1 ,  0
       0     0.1       0      80    0.05       0     160     0.1       0
     200    0.04       0     330     0.1       0   406.2   0.045       0
   435.6     0.1       0  661.33    0.12       0
#XS Ineff= 2 , 0
          363.32 1664.35
Permanent Ineff=
       F       F
Bank Sta=406.2,435.6
XS Rating Curve= 0 ,0
Exp/Cntr=0.3,0.1

Type RM Length L Ch R = 1 ,7203    ,255.3,259.4,261.6
XS GIS Cut Line= 3
     2082264.541      241246.222     2082450.739      241625.128
     2082511.936      241936.326
#Sta/Elev= 30
       0 1704.85    16.4 1701.63    42.6 1694.46    62.2 1692.94    85.1 1689.29
    98.2 1689.22   160.4 1682.51   186.6    1678   222.6 1663.34   255.3  1663.2
   258.6 1662.34   265.1 1658.51   268.4 1657.52   284.7 1654.49   327.3 1655.02
   353.5 1651.51   389.5  1650.3     396 1649.37   402.6 1649.79   405.8 1650.95
   422.2 1663.56   438.5 1671.91   441.8 1674.04   448.3 1679.79   451.6 1681.56
     553 1730.94   592.2 1747.69   670.7 1767.28   709.9 1772.78   739.3 1774.77
#Mann= 8, -1 ,  0
       0     0.1       0     220    0.04       0     330     0.1       0
   389.5   0.045       0   405.8     0.1       0  442.18    0.12       0
  502.18     0.1       0  542.18    0.12       0
#XS Ineff= 2 , 0
          332.38 1659.78
Permanent Ineff=
       F       F
Bank Sta=389.5,405.8
XS Rating Curve= 0 ,0
Exp/Cntr=0.3,0.1

Type RM Length L Ch R = 1 ,6943    ,261.7,263.5,262.2
XS GIS Cut Line= 3
     2082071.218      241296.538      2082196.24      241642.698
     2082301.695      241990.338
#Sta/Elev= 30
       0 1711.43   110.7 1680.39     127 1677.32   156.3 1668.04   188.9  1663.5
   231.2 1660.43     241 1655.66   244.3 1654.99   257.3 1656.04   273.6 1656.08
   280.1 1655.24   293.1 1651.17   302.9 1649.91   351.8 1647.56   371.3 1646.52
   375.5 1647.61   400.8 1660.48   420.4 1673.28   449.9 1686.36     476 1699.93
   505.5  1710.3   531.7 1717.65   544.8 1722.64   574.2 1730.56   603.7 1735.96
     620 1740.31   649.5 1744.95   669.1  1746.6     692 1747.44   731.3 1747.47
#Mann= 7, -1 ,  0
       0     0.1       0     160    0.06       0     260     0.1       0
   351.8   0.045       0   375.5    0.12       0  468.05     0.1       0
  578.05    0.12       0
Bank Sta=351.8,375.5
XS Rating Curve= 0 ,0
Exp/Cntr=0.3,0.1

Type RM Length L Ch R = 1 ,6680    ,238.3,235.7,232.3
XS GIS Cut Line= 3
     2081832.249      241366.013     2081953.343      241741.013
     2082194.228      242009.243
#Sta/Elev= 30
       0 1718.69    22.8 1713.23    48.8 1703.87    91.2 1691.26   120.5 1685.71
   179.1 1672.78   192.2  1671.4   198.7 1669.37   201.9 1666.78   205.2 1665.27
   218.2 1664.69     254 1660.72     267 1656.63   280.1 1650.08   306.1 1650.31
   319.2 1646.82   338.7 1644.64   348.5 1642.91   358.2 1643.03     368 1644.84
   387.6 1647.07   407.2 1652.05   426.8 1658.28   453.1  1664.4   525.2  1686.5
   580.9 1701.11   597.3 1707.77   679.2 1723.53   708.7 1727.15   754.6 1731.31
#Mann= 6, -1 ,  0
       0     0.1       0     190    0.04       0   338.7   0.045       0
     368    0.04       0     390    0.12       0  574.07     0.1       0
Bank Sta=338.7,368
XS Rating Curve= 0 ,0
Exp/Cntr=0.3,0.1

Type RM Length L Ch R = 1 ,6444    ,252.6,250.8,247.3
XS GIS Cut Line= 2
     2081591.568      241487.438     2081892.145      242156.378
#Sta/Elev= 30
       0 1716.13    52.4 1703.68    78.6  1695.2   134.2 1683.86   147.3 1679.96
   157.2 1675.53   176.8 1674.95   193.2 1670.31   206.3 1667.91   225.9  1661.9
   248.8 1656.14   258.6 1650.21   261.9 1649.38   271.7 1651.28   288.1 1651.15
   294.7 1649.97   304.5 1646.51   320.8 1642.44   353.6 1640.35   373.2 1639.65
   379.8 1640.45   399.4  1647.5   435.4 1656.66   481.3  1664.6   500.9 1669.81
   599.1 1683.59   612.2  1684.9     645  1685.6   694.1  1682.8   733.4 1681.67
#Mann= 9, -1 ,  0
       0     0.1       0      60    0.04       0     280     0.1       0
   353.6   0.045       0   379.8     0.1       0     390    0.12       0
     450     0.1       0     690    0.05       0     710     0.1       0
Bank Sta=353.6,379.8
XS Rating Curve= 0 ,0
Exp/Cntr=0.3,0.1

Type RM Length L Ch R = 1 ,6193    ,247.5,249.5,247.7
XS GIS Cut Line= 3
     2081327.879       241600.71     2081516.684      241919.141
     2081704.652      242230.467
#Sta/Elev= 30
       0 1711.56    22.9 1706.62    45.9 1700.27      59 1697.89    68.8 1693.54
    91.7 1692.46   104.8 1686.64   147.4 1675.52   176.9 1671.61   229.3 1662.21
   252.3 1656.42   265.4  1651.5   291.6 1652.09   304.7 1645.91   311.2 1643.91
   357.1 1636.38   373.5 1634.61   383.3 1636.23   399.7 1638.99   445.6 1653.08
   461.9 1655.13   481.6 1656.44   501.2 1655.14   517.6 1655.61   560.2 1663.48
   619.2  1668.6   648.7 1667.84   671.6 1662.31   681.4 1661.62   733.9 1668.27
#Mann= 9, -1 ,  0
       0    0.04       0     110     0.1       0     280    0.04       0
     300     0.1       0   357.1   0.045       0   383.3     0.1       0
   390.2    0.12       0   510.2    0.05       0  733.87     0.1       0
Bank Sta=357.1,383.3
XS Rating Curve= 0 ,0
Exp/Cntr=0.3,0.1

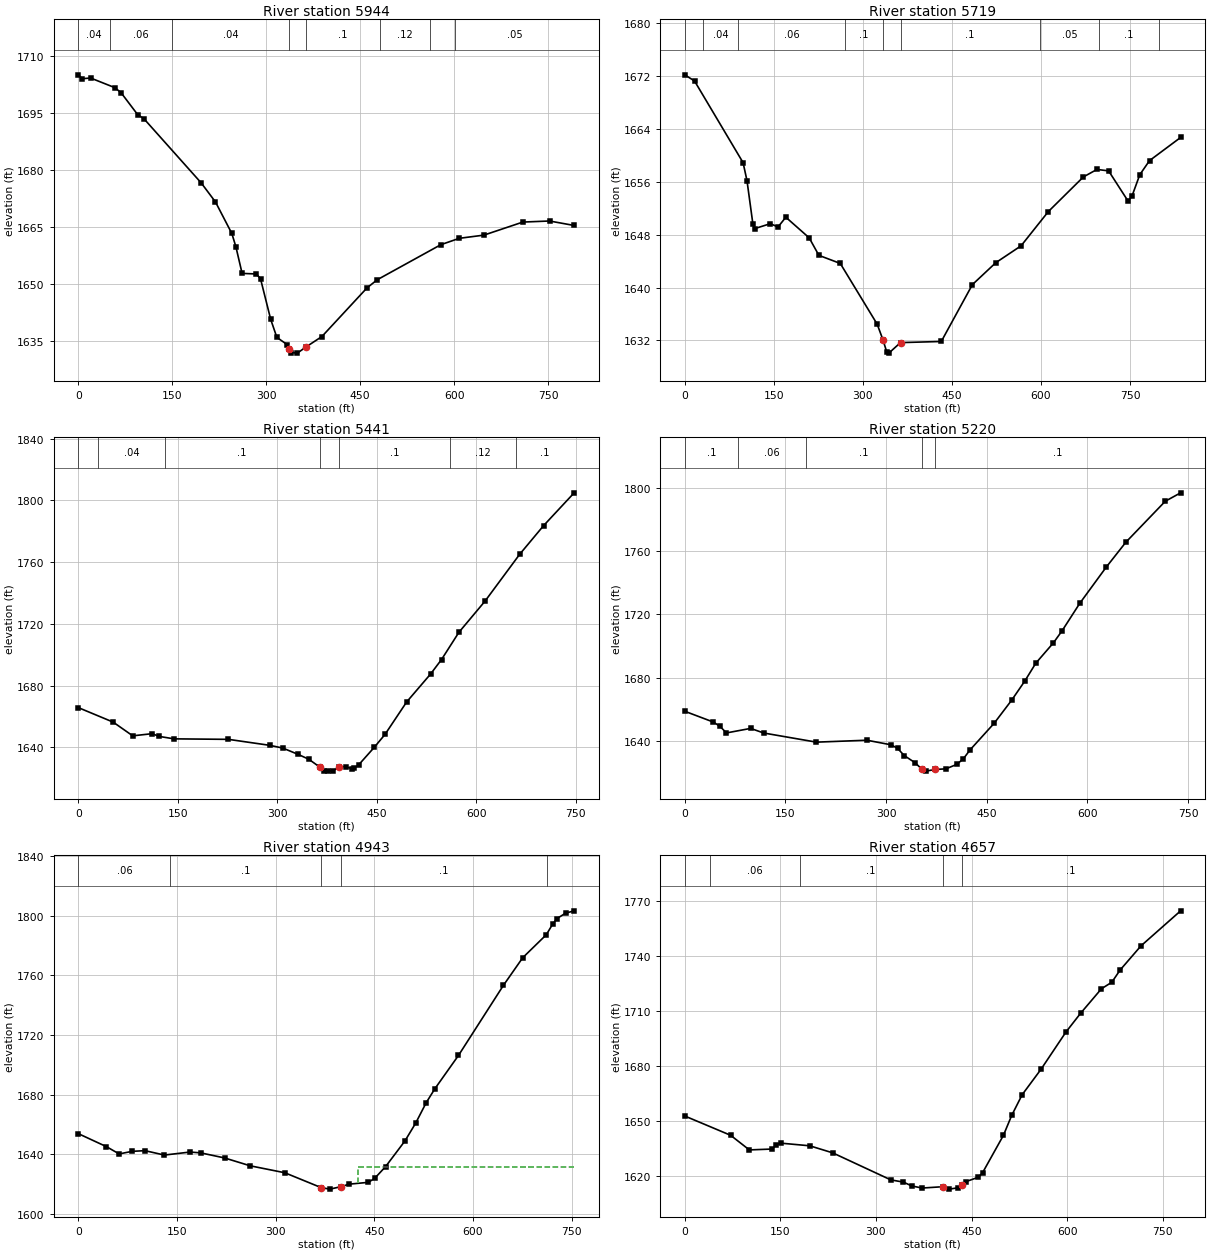
Type RM Length L Ch R = 1 ,5944    ,233.2,225.1,212.7
XS GIS Cut Line= 3
     2081112.197      241700.649      2081314.02      242048.305
     2081647.353      242250.128
#Sta/Elev= 30
       0 1705.04     6.5 1704.02    19.6  1704.2    58.8 1701.63    68.6 1700.25
    94.8 1694.54   104.6  1693.5   196.1 1676.59     219 1671.55   245.1 1663.25
   251.6 1659.74   261.5 1652.74   284.3 1652.59   290.9 1651.33   307.2  1640.6
     317 1635.89   333.4 1633.99   336.6 1632.88   339.9  1631.9   349.7 1631.74
   362.8 1633.28   388.9 1636.11   460.9 1648.92   477.3 1651.07   578.8  1660.3
   608.3 1661.98   647.6 1662.82   709.8 1666.26   752.4 1666.54   791.7 1665.36
#Mann= 8, -1 ,  0
       0    0.04       0      50    0.06       0     150    0.04       0
   336.6   0.045       0   362.8     0.1       0  481.99    0.12       0
  561.99     0.1       0  601.99    0.05       0
Bank Sta=336.6,362.8
XS Rating Curve= 0 ,0
Exp/Cntr=0.3,0.1

Type RM Length L Ch R = 1 ,5719    ,264.4,278,293.4
XS GIS Cut Line= 3
     2080870.009      241981.899     2081248.916      242239.711
     2081625.218      242263.149
#Sta/Elev= 30
       0 1672.13    16.4  1671.2    98.2 1658.86   104.8 1656.13   114.6 1649.67
   117.8  1648.9     144 1649.64   157.1 1649.15   170.2 1650.62   209.5 1647.51
   225.9 1644.86   261.9 1643.64   324.1 1634.46   333.9 1632.08   340.4 1630.21
   343.7 1630.09   363.4 1631.68   432.1 1631.85   484.5 1640.44   523.9 1643.75
   566.5  1646.3   612.4 1651.47   671.4  1656.7   694.4 1657.84     714 1657.62
   746.8 1653.05   753.4 1653.82   766.5 1657.04   782.9 1659.17   835.3 1662.67
#Mann= 9, -1 ,  0
       0     0.1       0      30    0.04       0      90    0.06       0
     270     0.1       0   333.9   0.045       0   363.4     0.1       0
   598.3    0.05       0   698.3     0.1       0   798.3    0.05       0
Bank Sta=333.9,363.4
XS Rating Curve= 0 ,0
Exp/Cntr=0.3,0.1

Type RM Length L Ch R = 1 ,5441    ,216.2,221.3,225.6
XS GIS Cut Line= 2
     2080836.155      242011.847     2081110.895      242707.159
#Sta/Elev= 30
       0 1665.74    52.5 1656.35      82 1647.46   111.5 1648.86   121.3 1647.13
   144.3  1645.5   226.2 1645.18   288.6 1641.31   308.2 1639.54   331.2 1635.48
   347.6 1632.27     364 1627.21   370.5 1624.86   377.1 1624.59   383.6 1624.94
   393.5 1626.99   403.3 1627.39   413.2 1626.13   416.4 1626.58     423  1628.8
     446 1639.91   462.4 1648.37   495.1 1669.44   531.2 1687.55   547.6 1696.89
   573.8 1714.52   613.2 1734.73   665.6 1765.16   701.7 1783.74   747.6 1804.91
#Mann= 7, -1 ,  0
       0     0.1       0      30    0.04       0     130     0.1       0
     364   0.045       0   393.5     0.1       0     560    0.12       0
     660     0.1       0
Bank Sta=364,393.5
XS Rating Curve= 0 ,0
Exp/Cntr=0.3,0.1

Type RM Length L Ch R = 1 ,5220    ,263.7,276.2,286.1
XS GIS Cut Line= 2
     2080710.374      242052.278     2080838.759      242780.076
#Sta/Elev= 30
       0 1658.66    42.5 1651.84    52.3 1649.17    62.1 1644.96    98.1 1647.82
   117.7  1644.9   196.2 1639.13   271.4 1640.35   307.4 1637.45   317.2 1635.17
     327 1630.67   343.4 1626.05   353.2 1622.07   359.7  1620.8   372.8 1621.85
   389.1 1622.24   405.5 1625.08   415.3 1628.67   425.1  1634.2   461.1 1651.08
   487.2 1665.68   506.9 1677.87   523.2  1689.1   549.4 1701.94   562.4 1709.61
   588.6 1726.88   627.8 1749.64   657.3 1765.54   716.1 1791.49     739 1796.82
#Mann= 5, -1 ,  0
       0     0.1       0      80    0.06       0     180     0.1       0
   353.2   0.045       0   372.8     0.1       0
Bank Sta=353.2,372.8
XS Rating Curve= 0 ,0
Exp/Cntr=0.3,0.1

Type RM Length L Ch R = 1 ,4943    ,275.2,286.4,299.1
XS GIS Cut Line= 3
      2080640.47      242047.934     2080513.468      242408.715
     2080410.241      242765.349
#Sta/Elev= 30
       0 1653.69    42.5    1645    62.1 1640.06    81.7 1641.79   101.3 1642.26
   130.8  1639.3     170 1641.33   186.3 1640.75   222.3 1637.36   261.5 1632.05
   313.8 1627.42   369.4 1617.38   382.5  1616.4   398.8    1618   411.8 1619.74
   441.1 1620.97   450.9 1623.82   467.2 1631.58   496.5 1648.76   512.8 1660.71
     529 1674.62   542.1 1683.91   577.9 1706.24   646.3  1753.4   675.6 1771.94
   711.4 1787.37   721.2 1794.58   727.7 1798.26   740.7 1801.88   753.8 1803.46
#Mann= 5, -1 ,  0
       0    0.06       0     140     0.1       0   369.4   0.045       0
   398.8     0.1       0  712.48   0.035       0
#XS Ineff= 2 , 0
                          425.21         1630.98
Permanent Ineff=
       F       F
Bank Sta=369.4,398.8
XS Rating Curve= 0 ,0
Exp/Cntr=0.3,0.1

Type RM Length L Ch R = 1 ,4657    ,223.6,235.8,242.9
XS GIS Cut Line= 3
     2080587.457      242010.545      2080258.03      242308.722
     2079993.198       242511.86
#Sta/Elev= 30
       0 1652.67    71.9 1642.16   101.3 1634.18   137.2 1634.66   143.8 1637.03
   150.3 1637.88     196 1636.43     232 1632.59   323.4 1617.82     343 1616.63
   356.1 1614.53   372.5 1613.38   405.1 1614.11   414.9 1612.79     428 1613.47
   434.5 1615.22   441.1 1616.87   460.7 1619.29   467.2 1621.68     500 1642.12
     513 1652.99   529.4 1664.28   558.9 1678.11   598.1 1698.46     621 1708.65
   653.8 1722.07   670.1 1725.64   683.2 1732.32   715.9 1745.48   778.1 1764.59
#Mann= 5, -1 ,  0
       0     0.1       0      40    0.06       0     180     0.1       0
   405.1   0.045       0   434.5     0.1       0
Bank Sta=405.1,434.5
XS Rating Curve= 0 ,0
Exp/Cntr=0.3,0.1

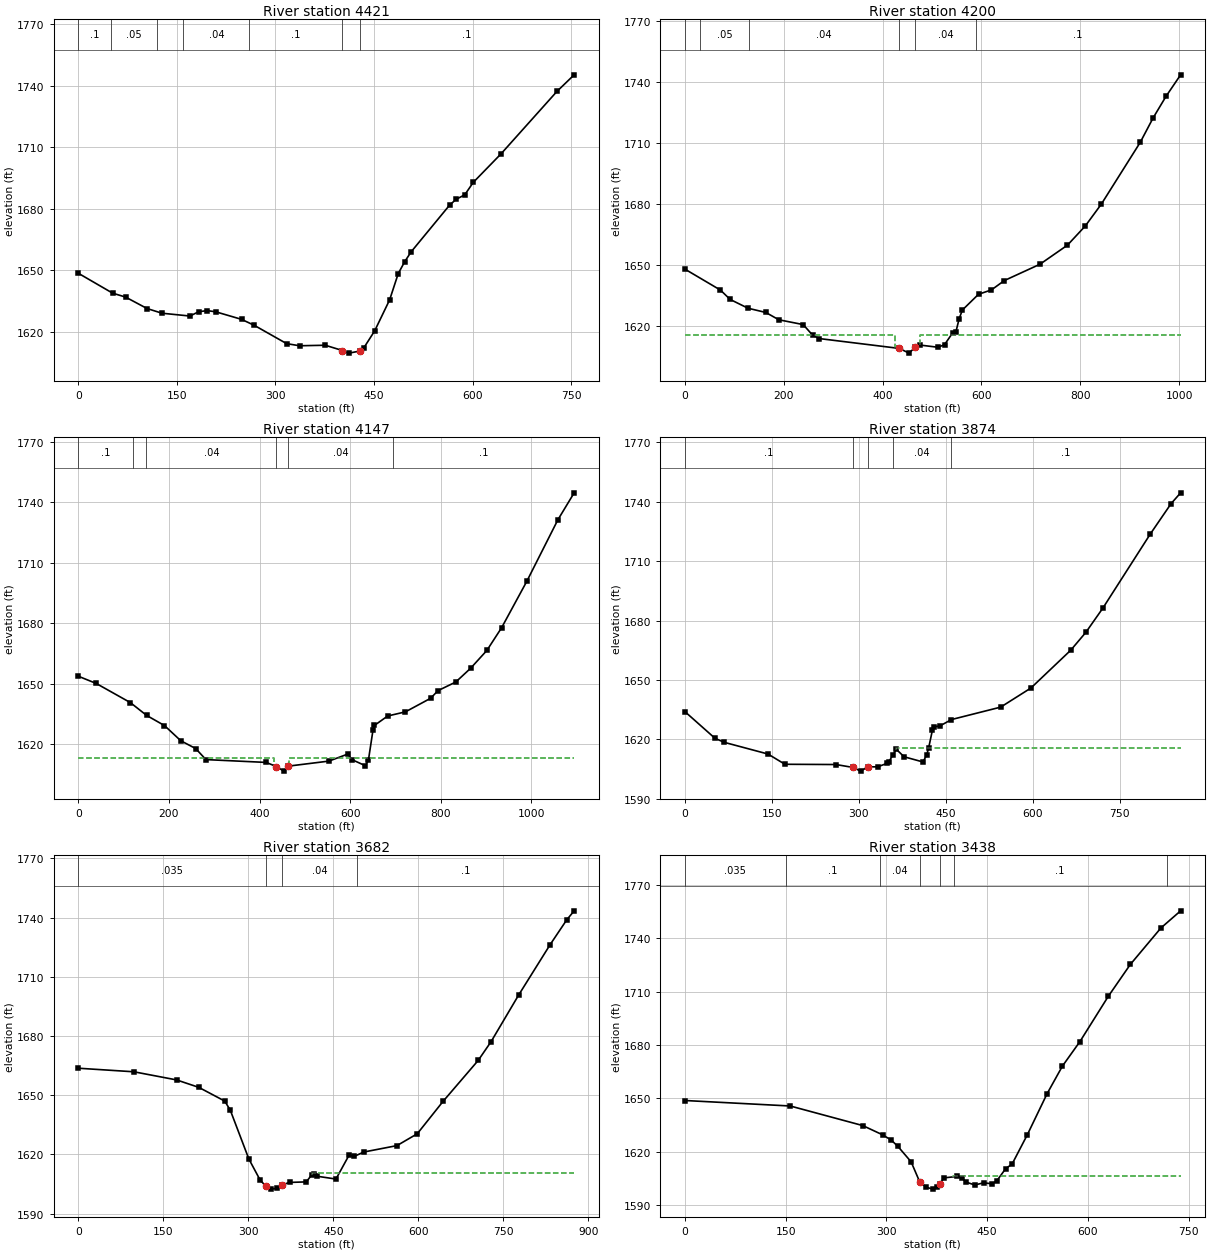
Type RM Length L Ch R = 1 ,4421    ,199.5,221.1,242
XS GIS Cut Line= 3
      2080539.28      241988.409     2080125.218      242149.868
     2079884.332       242345.18
#Sta/Elev= 30
       0 1648.46    52.3 1638.73    71.9 1636.83   104.6 1631.23   127.4 1628.94
   169.9 1627.57     183 1629.66   196.1 1630.22   209.1 1629.64   248.4 1625.95
     268 1622.99     317 1614.09   336.6 1613.05   375.8  1613.3     402 1610.72
   411.8 1609.45   428.1 1610.44   434.6 1612.08     451 1620.32   473.8 1635.51
   486.9 1648.34   496.7 1654.12   506.4  1658.9   565.2 1681.81     575 1684.59
   588.1 1686.79   601.1 1692.88   643.6  1706.9   728.4  1737.3   754.6  1745.4
#Mann= 7, -1 ,  0
       0     0.1       0      50    0.05       0     120    0.06       0
     160    0.04       0     260     0.1       0     402   0.045       0
   428.1     0.1       0
Bank Sta=402,428.1
XS Rating Curve= 0 ,0
Exp/Cntr=0.5,0.3

Type RM Length L Ch R = 1 ,4200    ,53.2,53.4,53.1
XS GIS Cut Line= 5
     2080521.051      241955.857     2080268.447      242013.149
     2080073.134      241918.097     2080004.124      241897.263
     2079863.499      242329.555
#Sta/Elev= 30
       0  1648.1    72.1 1637.76    91.8 1633.15   127.9 1628.84   163.9 1626.75
   190.2 1623.16   239.4  1620.8     259 1615.47     272 1613.92   434.1 1609.07
   453.5 1606.76   466.5 1609.76   476.2 1610.71   512.3 1609.64   525.4 1610.95
   541.8 1616.72   548.3 1617.16   554.9 1623.64   561.4 1627.95   594.1  1635.7
   620.3 1637.86   646.4 1642.45   718.4 1650.47     774 1659.86     810 1669.26
   842.7 1680.09   921.2  1710.4   947.3 1722.44   973.5 1733.08  1002.9 1743.61
#Mann= 6, -1 ,  0
       0     0.1       0      30    0.05       0     130    0.04       0
   434.1   0.045       0   466.5    0.04       0  588.32     0.1       0
#XS Ineff= 2 , 0
          424.65 1615.74  476.44         1615.74
Permanent Ineff=
       F       F
Bank Sta=434.1,466.5
XS Rating Curve= 0 ,0
Exp/Cntr=0.5,0.3

Type RM Length L Ch R = 1 ,4147    ,321.7,273,234.5
XS GIS Cut Line= 5
     2080543.186       241907.68     2080290.582      241964.972
      2080095.27       241869.92     2079979.384       241845.18
     2079837.457      242324.347
#Sta/Elev= 30
       0 1653.75    39.3 1650.19   114.8 1640.68   150.8 1634.31   190.2 1629.28
   226.2 1621.75     259 1617.89   281.7 1612.41   414.6 1611.01   437.3 1608.96
   453.5 1606.69   463.3 1609.16   553.1 1611.66   594.7 1615.14   604.5 1612.34
   633.9 1609.34   640.5 1612.35   650.3 1626.85   653.5 1629.34   682.9 1634.03
   722.1 1636.09   777.6 1642.81     794 1646.61   833.2 1650.88   865.8 1657.67
   901.8 1666.54   934.4 1677.82     990 1700.84  1058.5  1731.3  1094.5  1744.7
#Mann= 6, -1 ,  0
       0     0.1       0     120    0.05       0     150    0.04       0
   437.3   0.045       0   463.3    0.04       0  694.73     0.1       0
#XS Ineff= 2 , 0
          432.46 1613.08  466.02         1612.96
Permanent Ineff=
       F       F
Bank Sta=437.3,463.3
XS Rating Curve= 0 ,0
Exp/Cntr=0.5,0.3

Type RM Length L Ch R = 1 ,3874    ,209.9,191.8,161.4
XS GIS Cut Line= 3
     2079980.686      241483.201      2079945.53      241839.972
      2079820.53       242320.44
#Sta/Elev= 30
       0 1634.12    52.2 1620.56    68.4 1618.53   143.4 1612.66   172.7 1607.48
   260.7 1607.35   290.1 1605.88   303.1 1604.02   316.1 1606.21   332.4 1606.17
   348.7 1607.94     352 1608.74   358.5 1612.09     365 1614.98   378.1 1611.27
   410.8 1608.64   417.3 1612.35   420.6 1615.89   427.1 1624.88   430.4 1626.38
   440.2 1626.89   459.8 1630.06   544.7 1636.34   596.9    1646   665.5 1665.08
   691.6 1674.11     721 1686.38   802.7 1723.76   838.6 1739.12     855 1744.56
#Mann= 5, -1 ,  0
       0     0.1       0   290.1   0.045       0   316.1     0.1       0
   358.5    0.04       0   458.5     0.1       0
#XS Ineff= 2 , 0
                          364.44         1615.51
Permanent Ineff=
       F       F
Bank Sta=290.1,316.1
XS Rating Curve= 0 ,0
Exp/Cntr=0.3,0.1

Type RM Length L Ch R = 1 ,3682    ,235.2,244.4,252
XS GIS Cut Line= 3
     2079529.705      241618.624     2079886.936      241910.284
     2079808.811      242316.534
#Sta/Elev= 30
       0 1663.65    98.1 1661.84   173.4 1657.72   212.6 1653.95   258.4 1646.99
   268.2 1642.33   300.9 1617.65   320.5 1607.13   330.3 1603.98   340.2 1602.38
     350  1602.8   359.8  1604.6   372.9 1605.78   402.3 1606.05   412.1 1609.76
   415.4 1610.02   421.9 1608.88   454.6 1607.49   477.5 1619.48   487.2 1619.02
   503.5 1621.17   562.2 1624.43     598 1630.42   643.6 1646.86   705.5 1667.58
   728.3 1677.11   777.1 1700.81   832.5 1726.28   861.8 1738.84   874.9 1743.41
#Mann= 4, -1 ,  0
       0   0.035       0   330.3   0.045       0   359.8    0.04       0
  491.17     0.1       0
#XS Ineff= 2 , 0
                          412.36         1610.41
Permanent Ineff=
       F       F
Bank Sta=330.3,359.8
XS Rating Curve= 0 ,0
Exp/Cntr=0.3,0.1

Type RM Length L Ch R = 1 ,3438    ,256.2,262.7,267.4
XS GIS Cut Line= 3
     2079434.813      241692.324     2079682.509      242100.388
     2079736.523      242355.293
#Sta/Elev= 30
       0 1648.86   156.9 1645.78   264.8  1634.8   294.3 1629.62   307.3 1626.64
   317.2 1623.09   336.8 1614.46   349.8 1603.03   359.6 1600.16   369.5 1599.14
     376 1600.23   379.3 1601.98   385.8 1605.46   405.4 1606.25     412 1605.48
   418.5  1603.1   431.6 1601.46   444.7 1602.69   457.7 1602.12   464.3 1603.78
   477.4 1610.57   487.1 1613.21   509.9 1629.75   539.2  1652.7     562 1668.17
   588.1 1681.95   630.4 1707.39     663 1725.17   708.6 1745.66   737.9 1755.27
#Mann= 7, -1 ,  0
       0   0.035       0     150     0.1       0     290    0.04       0
   349.8   0.045       0   379.3    0.04       0     400     0.1       0
  717.36   0.035       0
#XS Ineff= 2 , 0
                          398.49          1606.4
Permanent Ineff=
       F       F
Bank Sta=349.8,379.3
XS Rating Curve= 0 ,0
Exp/Cntr=0.3,0.1

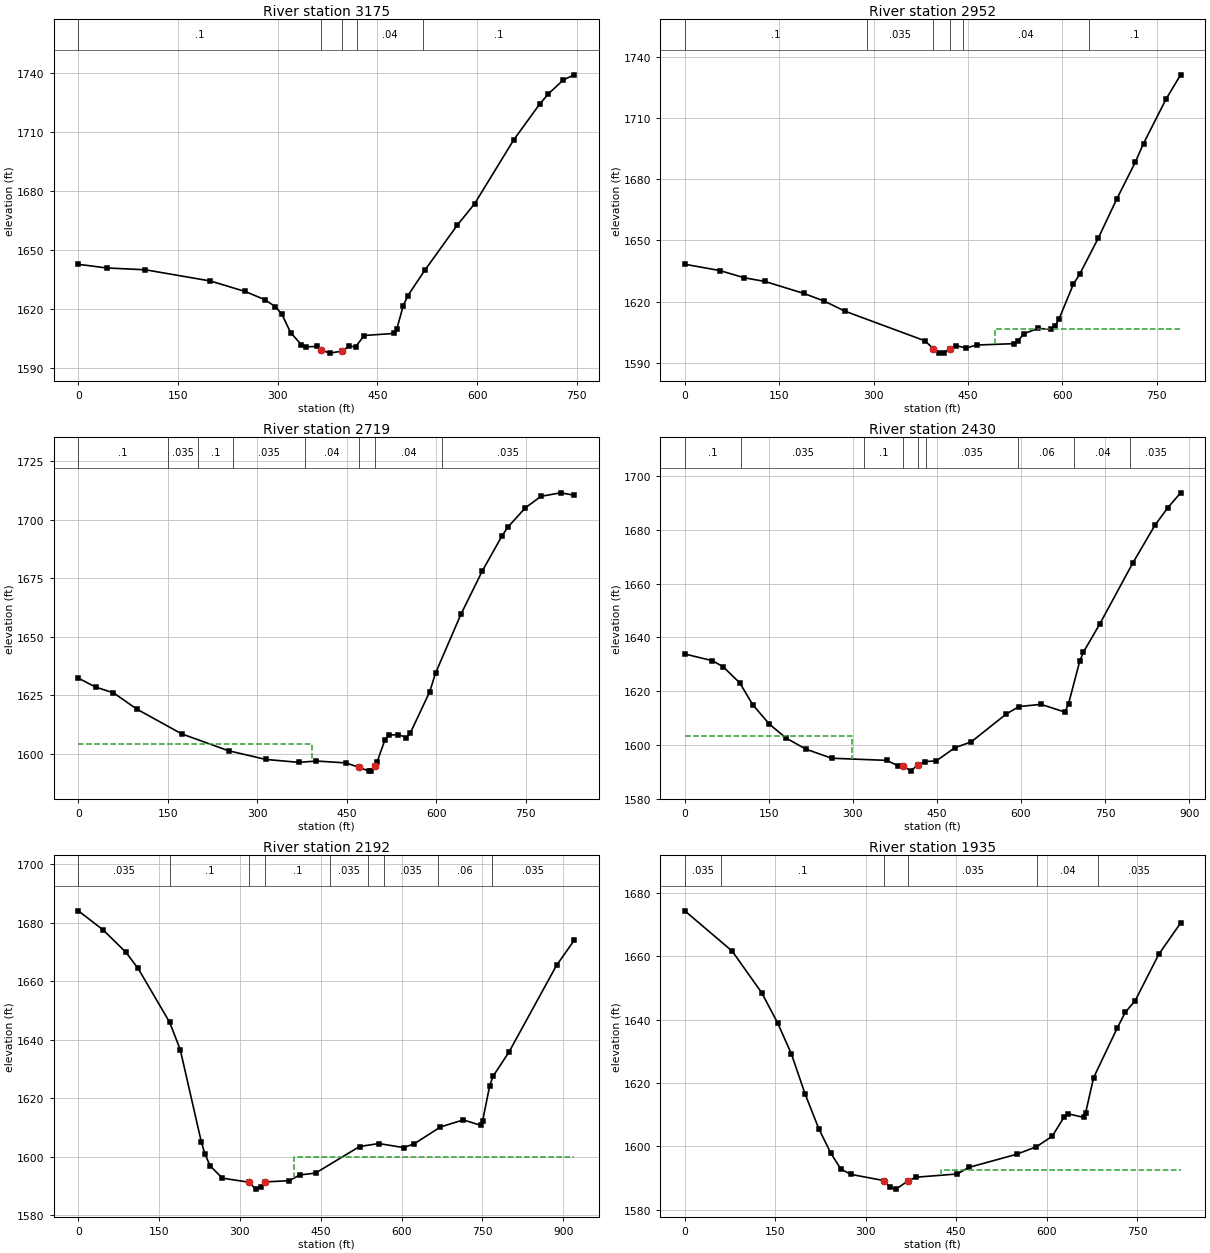
Type RM Length L Ch R = 1 ,3175    ,213.8,223.3,231.3
XS GIS Cut Line= 3
     2079390.843      241724.086     2079366.103      242052.211
     2079499.019      242447.305
#Sta/Elev= 30
       0 1642.52    42.4 1640.66     101 1639.72   198.7 1634.03   250.9  1628.7
   280.2 1624.57   296.5 1620.96   306.2 1617.13   319.3  1607.8   335.6 1601.55
   342.1 1600.52   358.4 1600.73   364.9 1599.06   377.9 1597.33   397.4 1598.38
   407.2 1600.89     417 1600.51     430 1606.29   475.6 1607.38   478.9 1609.38
   488.6  1621.2   495.2 1626.31   521.2 1639.47     570  1662.4   596.1 1673.31
   654.7 1705.68   693.8 1723.92   706.8 1729.12   729.6 1736.29   745.9 1738.91
#Mann= 5, -1 ,  0
       0     0.1       0   364.9   0.045       0   397.4     0.1       0
  419.06    0.04       0  519.06     0.1       0
Bank Sta=364.9,397.4
XS Rating Curve= 0 ,0
Exp/Cntr=0.3,0.1

Type RM Length L Ch R = 1 ,2952    ,214.7,232.4,241.6
XS GIS Cut Line= 3
     2079356.989      241739.711     2079170.791      242073.045
     2079172.093      242479.295
#Sta/Elev= 30
       0 1638.33    55.5 1635.26    94.6  1631.7   127.3 1629.92   189.3 1624.03
   221.9 1620.26   254.5 1615.37   381.8 1600.83   394.9 1597.02   404.8 1594.82
   411.3 1594.94   421.1 1596.91     431 1598.48   447.3 1597.33   463.7 1598.77
   522.7 1599.46   529.2 1600.62   539.1 1604.37     562 1606.94   581.7 1606.42
   588.2  1607.9   594.8 1611.51   617.7 1628.63   627.5  1633.4     657 1650.98
   686.5 1670.22     716 1688.28   729.1 1697.44   765.1 1719.27   788.1 1731.07
#Mann= 6, -1 ,  0
       0     0.1       0     290   0.035       0   394.9   0.045       0
   421.1   0.035       0  441.81    0.04       0  641.81     0.1       0
#XS Ineff= 2 , 0
                          492.84         1606.78
Permanent Ineff=
       F       F
Bank Sta=394.9,421.1
XS Rating Curve= 0 ,0
Exp/Cntr=0.3,0.1

Type RM Length L Ch R = 1 ,2719    ,274,288.8,298.5
XS GIS Cut Line= 2
     2079221.869      241715.359     2078774.037      242415.668
#Sta/Elev= 30
       0 1632.27    29.4 1628.42    58.9 1626.01    98.2 1619.03   173.4 1608.47
     252 1601.26   314.2 1597.57   369.8 1596.31   399.3 1596.88   448.4 1596.08
   471.3 1594.13   487.6 1592.57   490.9  1592.7   497.4 1594.67   500.7 1596.37
   513.8 1605.73   520.4 1607.91   536.7 1608.18   549.8 1606.91   556.4 1608.76
   589.1 1626.43   598.9 1634.42   641.4 1659.52   677.4 1678.08   710.2 1692.96
     720 1696.71   749.4 1704.99   775.6  1709.9   808.4 1711.41   831.3  1710.4
#Mann= 8, -1 ,  0
       0     0.1       0     150   0.035       0     200     0.1       0
     260   0.035       0     380    0.04       0   471.3   0.045       0
   497.4    0.04       0     610   0.035       0
#XS Ineff= 2 , 0
          391.12 1604.04
Permanent Ineff=
       F       F
Bank Sta=471.3,497.4
XS Rating Curve= 0 ,0
Exp/Cntr=0.3,0.1

Type RM Length L Ch R = 1 ,2430    ,261.6,238.8,206.4
XS GIS Cut Line= 3
     2079203.343      241703.253     2078786.676      241910.284
     2078718.968      242324.347
#Sta/Elev= 30
       0 1633.81    49.2 1631.31    68.8 1628.99    98.3    1623   121.2 1614.92
   150.7 1607.74   180.2 1602.59   216.2 1598.37   262.1    1595   360.4  1594.2
   380.1 1592.22   389.9 1592.27     403  1590.2   416.1 1592.61   429.2 1593.76
   448.9 1594.03   481.7 1598.88   511.2  1601.1   573.4 1611.43   596.4 1614.24
   635.7 1615.06   678.3 1612.18   684.9 1615.36   704.6 1631.04   711.1  1634.4
   740.6 1645.02   799.6 1667.74   838.9 1681.71   861.9 1688.26   884.8 1693.81
#Mann= 9, -1 ,  0
       0     0.1       0     100   0.035       0     320     0.1       0
   389.9   0.045       0   416.1     0.1       0     430   0.035       0
  595.27    0.06       0  695.27    0.04       0  795.27   0.035       0
#XS Ineff= 2 , 0
          297.99 1603.22
Permanent Ineff=
       F       F
Bank Sta=389.9,416.1
XS Rating Curve= 0 ,0
Exp/Cntr=0.3,0.1

Type RM Length L Ch R = 1 ,2192    ,268.7,256.1,239.3
XS GIS Cut Line= 3
     2078750.105      241378.312     2078755.426      241795.701
     2078616.103      242278.774
#Sta/Elev= 30
       0 1684.11    45.7 1677.63      88    1670   110.9 1664.43   169.6 1645.95
   189.1 1636.67   228.3 1605.06   234.8 1601.08   244.6  1596.9   267.4  1592.7
   316.3 1591.34   329.4 1588.96   339.2  1589.8   345.7 1591.42   391.3 1591.84
   410.9  1593.8   440.3 1594.45   521.9 1603.53   557.8 1604.54   603.5 1603.17
   623.1 1604.42   672.1 1610.22   714.5 1612.62   747.2 1610.76   750.4 1612.37
   763.5 1624.35     770 1627.63   799.4 1635.88   887.5 1665.46   920.2    1674
#Mann= 9, -1 ,  0
       0   0.035       0     170     0.1       0   316.3   0.045       0
   345.7     0.1       0  467.42   0.035       0  537.42     0.1       0
  567.42   0.035       0  667.42    0.06       0  767.42   0.035       0
#XS Ineff= 2 , 0
                          401.15         1600.09
Permanent Ineff=
       F       F
Bank Sta=316.3,345.7
XS Rating Curve= 0 ,0
Exp/Cntr=0.3,0.1

Type RM Length L Ch R = 1 ,1935    ,188.1,197.7,204.6
XS GIS Cut Line= 4
     2078488.499      241489.711     2078496.313      241757.939
     2078612.197      241928.513     2078583.551      242274.868
#Sta/Elev= 30
       0  1674.3    78.5  1661.6   127.6 1648.43   153.8 1638.98   176.7 1629.17
   199.6 1616.44   222.5 1605.41   242.2 1597.81   258.5  1592.9   274.9 1591.17
   330.5 1589.18   340.4 1587.04   350.2  1586.5   369.8 1589.05   382.9 1590.25
   451.6 1591.28   471.3 1593.37     550 1597.49   582.8 1599.85     609 1603.14
   628.6 1609.15   635.2 1610.28   661.4 1609.13   664.7 1610.66   677.8 1621.65
   717.2 1637.41   730.3 1642.28   746.7 1645.94     786 1660.63   822.1 1670.45
#Mann= 6, -1 ,  0
       0   0.035       0      60     0.1       0   330.5   0.045       0
   369.8   0.035       0  584.56    0.04       0  684.56   0.035       0
#XS Ineff= 2 , 0
                          424.93         1592.47
Permanent Ineff=
       F       F
Bank Sta=330.5,369.8
XS Rating Curve= 0 ,0
Exp/Cntr=0.3,0.1