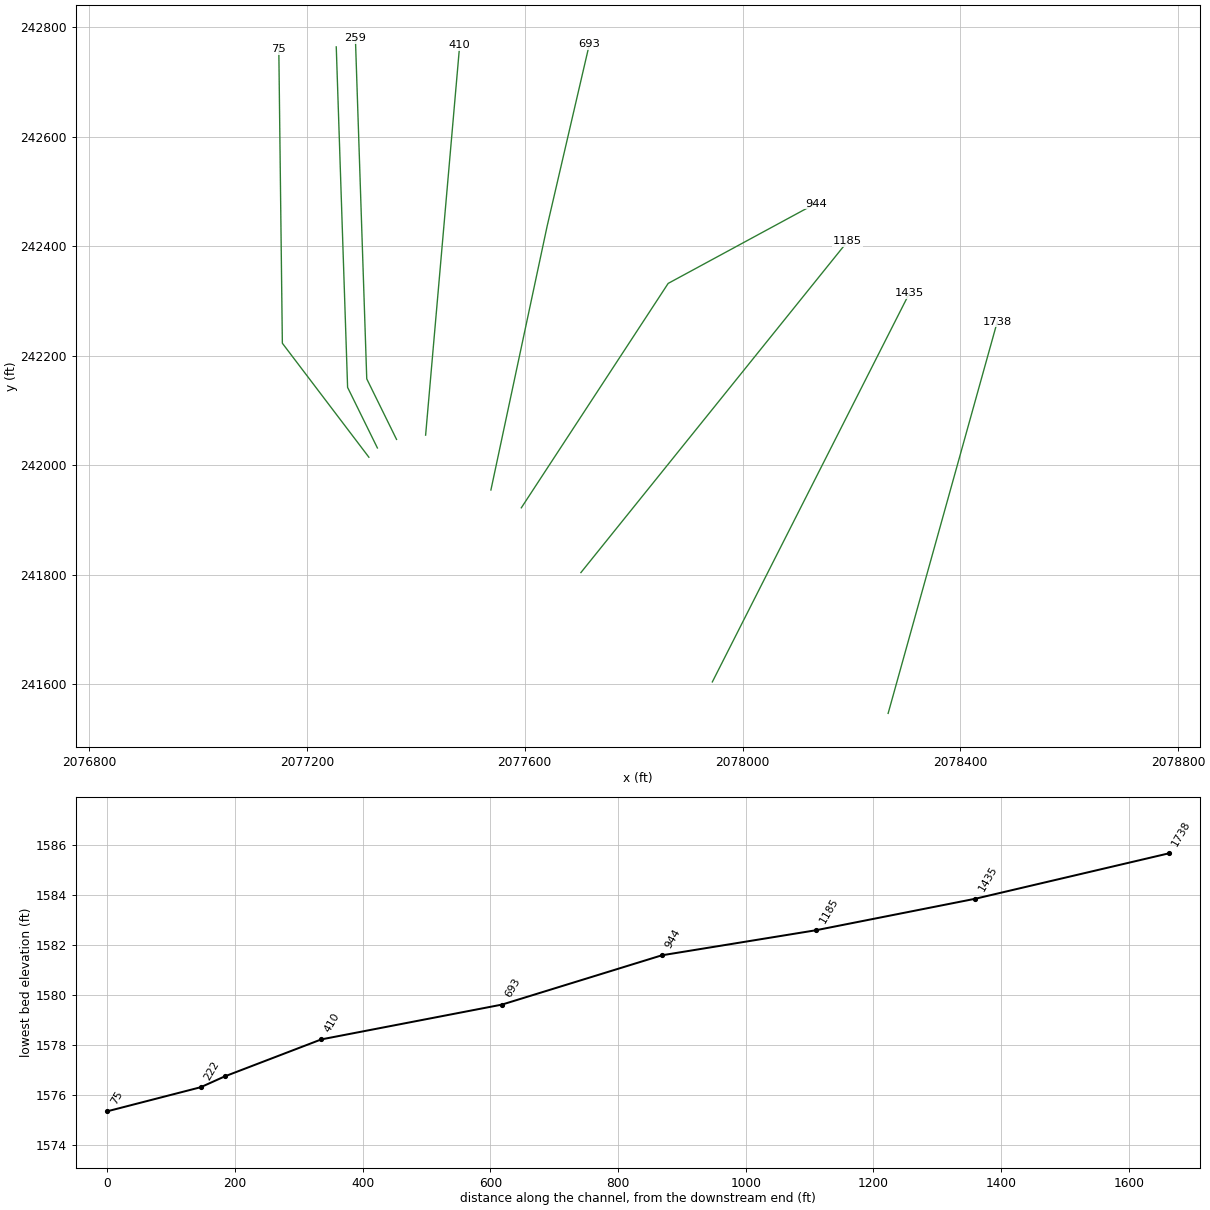
HEC-RAS study BROADRUN.prj: BROADRUN

--- BROADRUN.g01 (geometry) --- (continued)

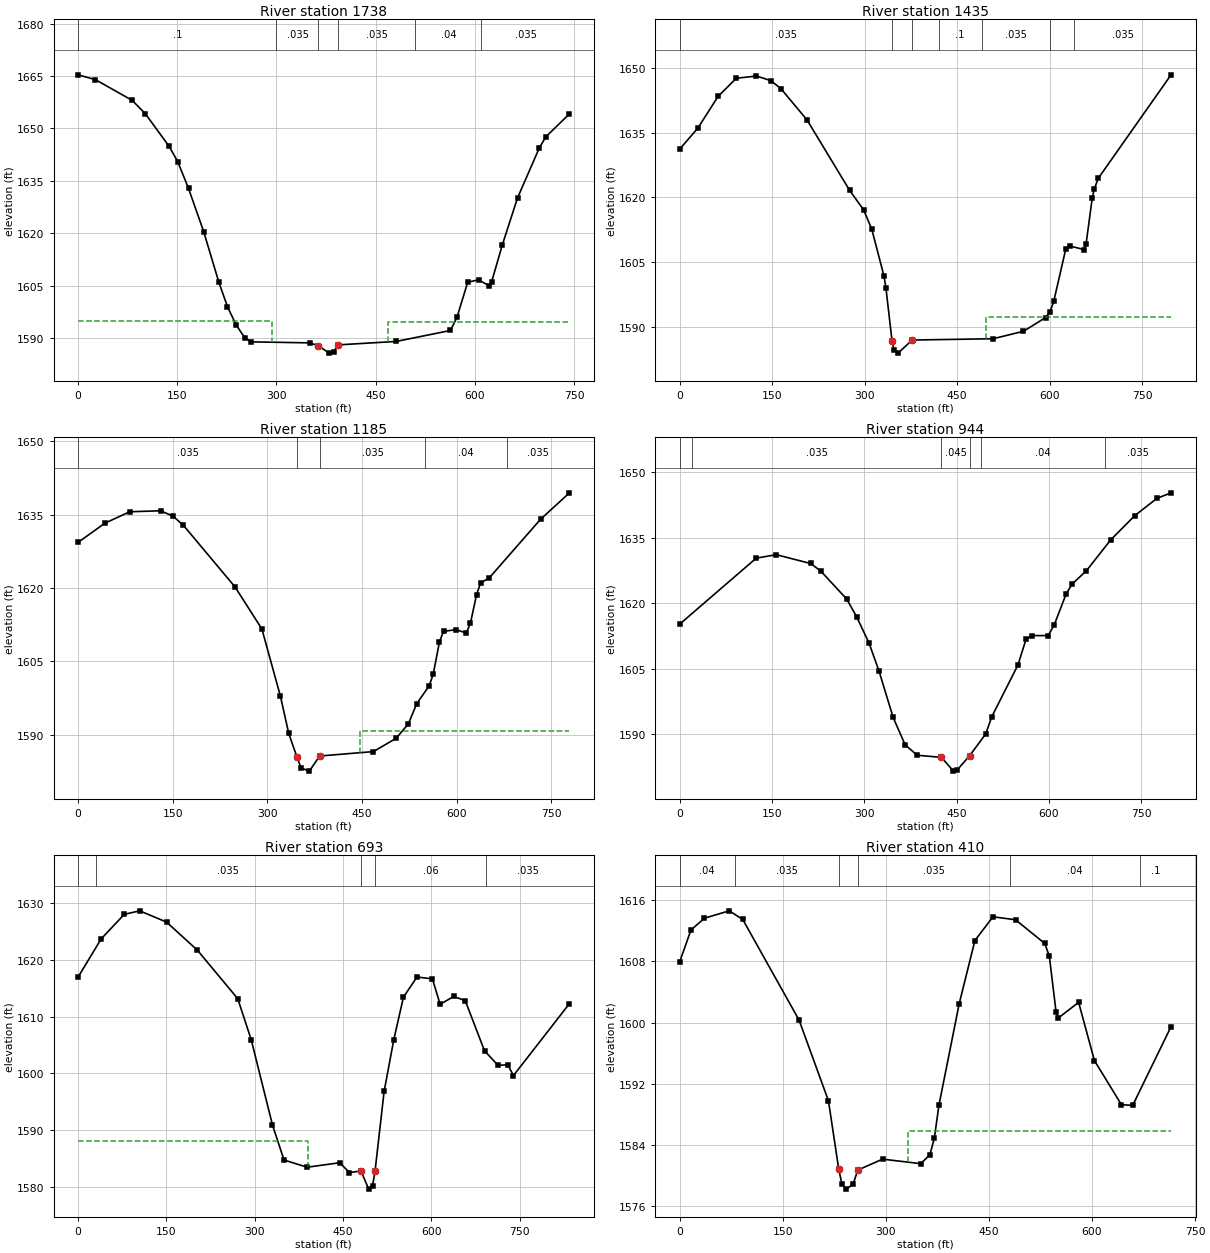
Type RM Length L Ch R = 1 ,1738    ,299.7,302.6,285.3
XS GIS Cut Line= 2
     2078267.339      241546.254     2078467.666      242261.847
#Sta/Elev= 30
       0 1665.37    26.2 1663.99    81.8 1658.05   101.5 1654.27   137.5 1644.92
   150.6 1640.52     167 1632.82   189.9 1620.46   212.8 1605.99   225.9 1598.94
     239 1593.72   252.1 1590.06   261.9 1588.88   350.3 1588.59   363.4 1587.76
   379.7 1585.65   386.3 1585.91   392.8 1588.01   481.2    1589   563.1 1592.14
   572.9 1595.87   589.2 1605.98   605.6 1606.63     622 1604.91   625.2 1605.96
   641.6 1616.69   664.5  1630.1   697.3 1644.35   707.1 1647.56   743.1  1654.2
#Mann= 6, -1 ,  0
       0     0.1       0     300   0.035       0   363.4   0.045       0
   392.8   0.035       0     510    0.04       0     610   0.035       0
#XS Ineff= 2 , 0
          293.41 1594.78  468.77         1594.57
Permanent Ineff=
       F       F
Bank Sta=363.4,392.8
XS Rating Curve= 0 ,0
Exp/Cntr=0.3,0.1

Type RM Length L Ch R = 1 ,1435    ,252.3,250,239.9
XS GIS Cut Line= 2
      2077944.58      241603.734     2078306.207       242313.93
#Sta/Elev= 30
       0 1631.19    29.5 1636.07    62.3 1643.43    91.8 1647.64   124.6 1648.16
   147.6 1647.11     164 1645.26   206.6 1637.96   275.5 1621.66   298.4 1617.08
   311.6 1612.59   331.2 1601.83   334.5 1599.03   344.4 1586.71   347.5 1584.63
   354.2 1583.84   377.2 1586.88   508.4 1587.18   557.6 1588.91   593.6  1592.1
   600.2  1593.3   606.7 1595.84   626.4 1608.11     633 1608.69   655.9 1607.88
   659.2 1609.22   669.1 1619.75   672.3 1621.88   678.9 1624.41     797 1648.44
#Mann= 7, -1 ,  0
       0   0.035       0   344.4   0.045       0   377.2   0.035       0
     420     0.1       0     490   0.035       0     600    0.04       0
     640   0.035       0
#XS Ineff= 2 , 0
                          496.28         1592.17
Permanent Ineff=
       F       F
Bank Sta=344.4,377.2
XS Rating Curve= 0 ,0
Exp/Cntr=0.3,0.1

Type RM Length L Ch R = 1 ,1185    ,233.7,241.2,243.4
XS GIS Cut Line= 2
     2077703.292      241803.598     2078192.926      242408.982
#Sta/Elev= 30
       0 1629.33    42.5 1633.26    81.8 1635.59   130.9 1635.79   150.5 1634.67
   166.8 1632.83   248.6 1620.23   291.2 1611.64   320.6 1597.88   333.7 1590.31
   346.8 1585.44   353.3 1583.23   366.4 1582.58   382.8 1585.67   467.8 1586.57
   503.8 1589.27   523.4 1592.25   536.5 1596.36   556.2 1599.99   562.7  1602.4
   572.5 1608.97     579 1611.14   598.7 1611.49     615 1610.81   621.6 1612.78
   631.4 1618.67   637.9 1621.09     651    1622   732.8 1634.06   778.6 1639.46
#Mann= 5, -1 ,  0
       0   0.035       0   346.8   0.045       0   382.8   0.035       0
     550    0.04       0     680   0.035       0
#XS Ineff= 2 , 0
                          446.99         1590.83
Permanent Ineff=
       F       F
Bank Sta=346.8,382.8
XS Rating Curve= 0 ,0
Exp/Cntr=0.3,0.1

Type RM Length L Ch R = 1 ,944     ,242.1,250.6,256.9
XS GIS Cut Line= 3
      2077593.89      241921.968     2077863.499      242332.159
     2078134.339      242478.156
#Sta/Elev= 30
       0 1615.19   124.4 1630.29   157.1 1631.08   212.7 1629.07   229.1 1627.37
   271.6 1620.91     288 1616.76   307.6 1610.92     324 1604.45   346.9 1593.87
   366.5 1587.58   386.1 1585.21   425.4 1584.73     445 1581.58   451.5 1581.93
   471.2  1585.1   497.4 1590.08   507.2 1594.01   549.8 1605.86   562.9 1611.75
   572.7 1612.58   598.9 1612.58   608.7 1615.02   628.3 1622.18   638.2 1624.42
   661.1 1627.42   700.4 1634.45   739.6 1640.01   775.6 1643.96   798.6 1645.23
#Mann= 6, -1 ,  0
       0    0.04       0      20   0.035       0   425.4   0.045       0
   471.2   0.035       0     490    0.04       0  690.86   0.035       0
Bank Sta=425.4,471.2
XS Rating Curve= 0 ,0
Exp/Cntr=0.3,0.1

Type RM Length L Ch R = 1 ,693     ,277.5,283,277.2
XS GIS Cut Line= 3
     2077538.064      241954.546     2077641.346      242437.095
     2077718.786      242769.217
#Sta/Elev= 30
       0 1616.97    39.2 1623.69    78.4 1628.01   104.6 1628.63   150.3 1626.64
   202.6 1621.69   271.2 1613.14   294.1 1605.88   330.1  1590.9   349.7 1584.74
   388.9 1583.47   444.5 1584.26   460.8 1582.51   480.4 1582.82   493.5 1579.61
     500 1580.17  504.27 1582.78   519.7 1596.83   536.1 1605.91   552.5 1613.42
   575.5 1616.97   601.7 1616.65   614.8 1612.16   637.8 1613.54   657.4 1612.82
   690.2 1603.98   713.2 1601.41   729.6 1601.51   739.4 1599.62   834.5 1612.29
#Mann= 5, -1 ,  0
       0    0.04       0      30   0.035       0   480.4   0.045       0
  504.27    0.06       0  693.48   0.035       0
#XS Ineff= 2 , 0
          389.68    1588
Permanent Ineff=
       F       F
Bank Sta=480.4,504.27
XS Rating Curve= 0 ,0
Exp/Cntr=0.3,0.1

Type RM Length L Ch R = 1 ,410     ,137.4,151.5,156.2
XS GIS Cut Line= 2
     2077418.186      242054.815     2077480.686      242767.055
#Sta/Elev= 30
       0 1607.93    16.4  1612.1    36.1 1613.65    72.2 1614.61    91.8 1613.48
   173.8 1600.31   216.5 1589.77  231.32  1580.9   236.1 1578.86   242.7 1578.22
   252.5  1578.9   259.1 1580.71   295.2 1582.14   350.9 1581.55     364  1582.7
   370.6 1584.89   377.2 1589.17   406.7 1602.45   429.6 1610.73   455.9 1613.83
   488.7 1613.44   531.3 1610.34   537.9 1608.67   547.7 1601.38     551  1600.6
   580.5 1602.64   603.5 1595.03   642.8 1589.26   659.2 1589.17     715 1599.47
#Mann= 6, -1 ,  0
       0    0.04       0      80   0.035       0  231.32   0.045       0
   259.1   0.035       0     480    0.04       0     670     0.1       0
#XS Ineff= 2 , 0
                          332.38         1585.87
Permanent Ineff=
       F       F
Bank Sta=231.32,259.1
XS Rating Curve= 0 ,0
Exp/Cntr=0.5,0.3

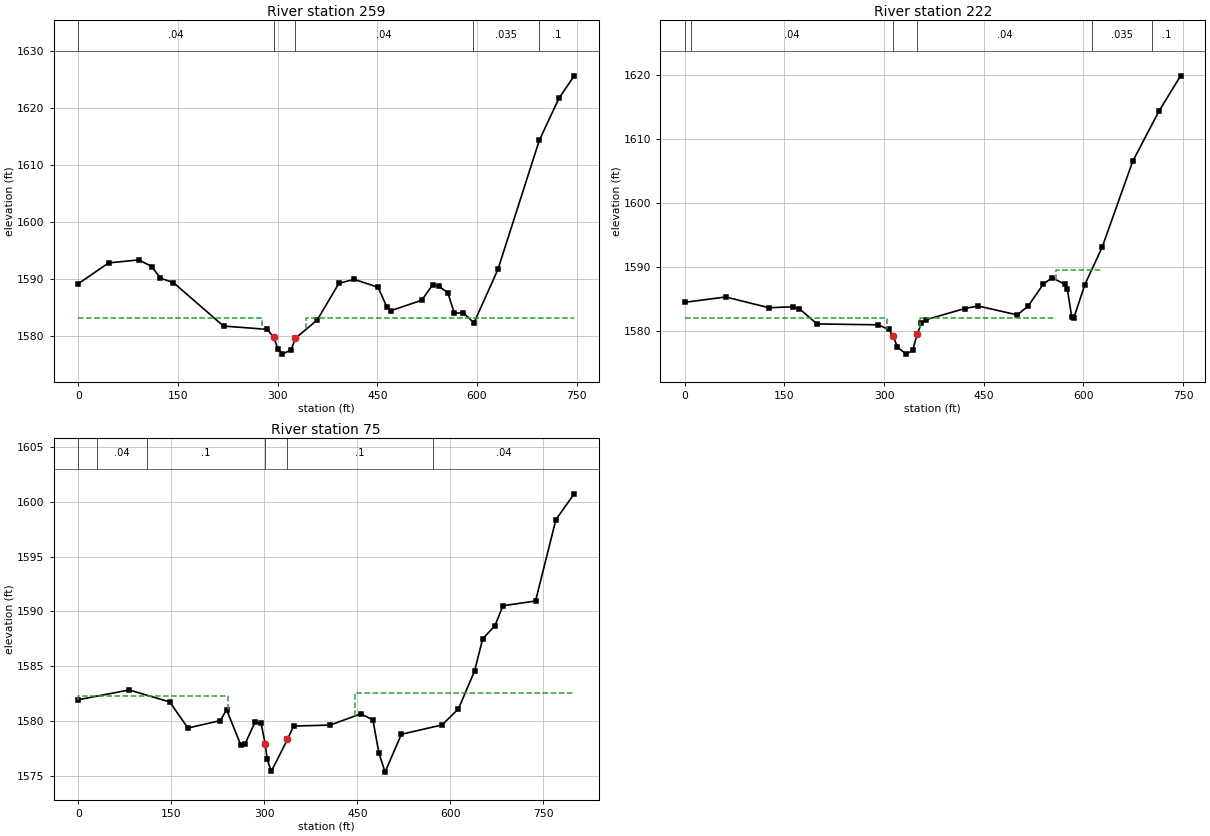
Type RM Length L Ch R = 1 ,259     ,43.6,37.4,36.1
XS GIS Cut Line= 3
     2077364.801      242047.003     2077310.114       242157.68
      2077289.28      242780.076
#Sta/Elev= 30
       0 1589.12    45.5 1592.77      91  1593.3   110.5 1592.14   123.4 1590.09
   143.1 1589.31   218.5 1581.67     284  1581.1   293.9 1579.74   300.4 1577.64
     307 1576.74   320.1 1577.48   326.7 1579.53   359.4 1582.72   392.2 1589.19
   415.2 1589.88   451.2 1588.48   464.3 1585.02   470.9  1584.4   516.8 1586.21
   533.2 1588.92     543 1588.64   556.1 1587.52   565.9 1583.91     579 1584.03
   595.4 1582.23   631.5 1591.64   693.8 1614.33   723.2 1621.68   746.2 1625.65
#Mann= 5, -1 ,  0
       0    0.04       0   293.9   0.045       0   326.7    0.04       0
  593.45   0.035       0  693.45     0.1       0
#XS Ineff= 2 , 0
             277 1583.13     343         1583.13
Permanent Ineff=
       F       F
Bank Sta=293.9,326.7
XS Rating Curve= 0 ,0
Exp/Cntr=0.5,0.3

Type RM Length L Ch R = 1 ,222     ,135.6,146.1,145.9
XS GIS Cut Line= 3
     2077329.645      242031.378     2077274.957      242142.055
     2077254.124      242764.451
#Sta/Elev= 30
       0 1584.41    61.7 1585.24   126.7 1583.56   162.8 1583.71   172.6 1583.39
   198.8 1581.03   290.6 1580.89     307 1580.18   313.6 1579.14   320.1 1577.38
   333.2 1576.31     343 1576.91   349.6 1579.42   356.2 1581.13   362.7 1581.68
   421.7 1583.44   441.4 1583.83   500.4 1582.44   516.8 1583.83   539.7 1587.27
   552.8 1588.25   572.5  1587.2   575.8 1586.42   582.3 1582.13   585.6 1581.99
     602 1587.16   628.2 1593.04   674.1 1606.44   713.4 1614.25   746.2  1619.8
#Mann= 6, -1 ,  0
       0   0.035       0      10    0.04       0   313.6   0.045       0
   349.6    0.04       0  613.45   0.035       0  703.45     0.1       0
#XS Ineff= 3 ,-1
       0     3051581.912  353.45     5581581.994  558.08   626.8 1589.48
Permanent Ineff=
       F       F       F
Bank Sta=313.6,349.6
XS Rating Curve= 0 ,0
Exp/Cntr=0.5,0.3

Type RM Length L Ch R = 1 ,75      ,92.4,75.4,56.4
XS GIS Cut Line= 3
      2077314.02      242014.451     2077155.166      242222.784
     2077148.655      242760.545
#Sta/Elev= 30
       0 1581.95    81.9 1582.84   147.4 1581.75   176.8 1579.37   229.2 1580.05
   239.1 1581.04     262 1577.83   268.6 1577.89   284.9 1579.88   294.8 1579.81
   301.3 1577.95   304.6 1576.54   311.2 1575.41   337.4 1578.34   347.2 1579.55
   406.3 1579.64   455.5 1580.66   475.1 1580.12     485 1577.06   494.8 1575.35
     521  1578.8   586.6 1579.65   612.9  1581.1   639.1 1584.55   652.2  1587.5
   671.9 1588.69     685 1590.52   737.5 1590.95   770.3 1598.36   799.8 1600.72
#Mann= 6, -1 ,  0
       0   0.035       0      30    0.04       0     110     0.1       0
   301.3   0.045       0   337.4     0.1       0  571.99    0.04       0
#XS Ineff= 2 , 0
          240.69  1582.3  445.85         1582.57
Permanent Ineff=
       F       F
Bank Sta=301.3,337.4
XS Rating Curve= 0 ,0
Exp/Cntr=0.3,0.1
Stream Node=BROADRUN        ,Main            , 0 , 0 ,Upstream end
Stream Node=BROADRUN        ,Main            , 0 , 1 ,Downstream end
LCMann Table=0

Chan Stop Cuts=-1
Use User Specified Reach Order=0
Composite Channel Slope=5